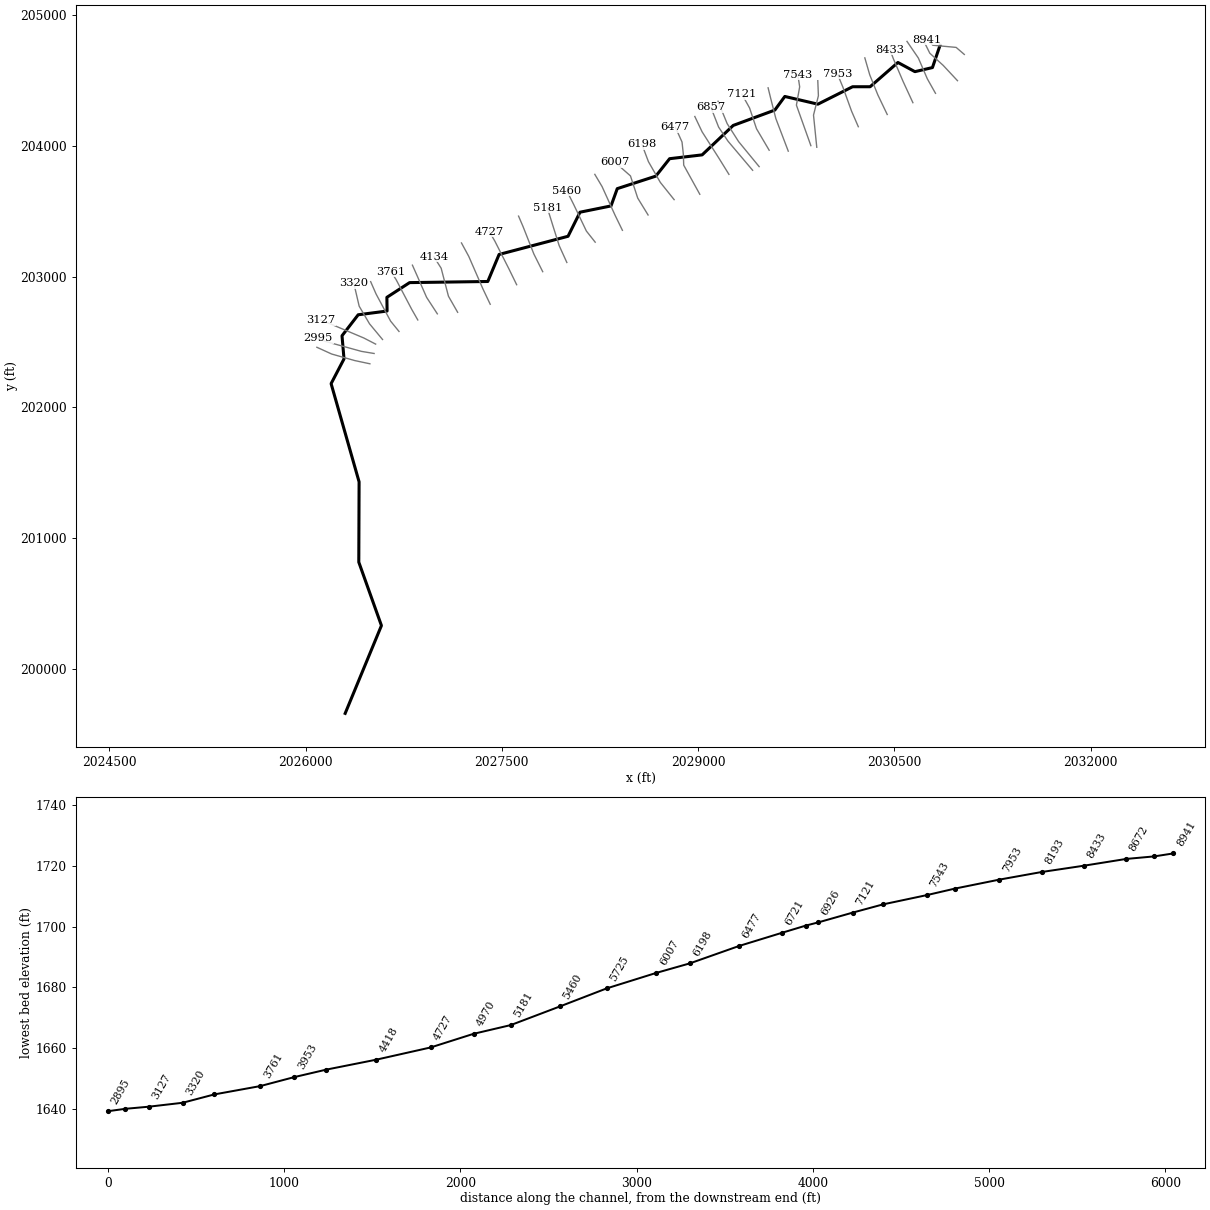
--- BRDSHWCK2_A.prj (project) ---

Proj Title=BRDSHWCK2_A
Current Plan=p01
Default Exp/Contr=0,0
English Units
Geom File=g01
Flow File=f01
Plan File=p01
BEGIN DESCRIPTION:
Stream Name: Bradshaw Creek
Flood Zone: Approximate
Summers County, West Virginia
HEC-RAS Version: 5.0.7
Hydrology Method:
Regression.
Model Notes:
END DESCRIPTION:
DSS Export Rating Curves= 0
DSS Export Rating Curve Sorted= 0
DSS Export Volume Flow Curves= 0
DXF OffsetX= 0
DXF OffsetY= 0
DXF ScaleX= 0
DXF ScaleY= 0

--- BRDSHWCK2_A.p01 (plan) ---

Plan Title=Floodplain
Program Version=5.07
Short Identifier=Floodplain
Geom File=g01
Flow File=f01
Subcritical Flow
K Sum by GR= 0
Std Step Tol= 0.01
Critical Tol= 0.01
Num of Std Step Trials= 20
Max Error Tol= 0.3
Flow Tol Ratio= 0.001
Split Flow NTrial= 30
Split Flow Tol= 0.02
Split Flow Ratio= 0.02
Log Output Level= 0
Friction Slope Method= 1
Unsteady Friction Slope Method= 2
Unsteady Bridges Friction Slope Method= 1
Parabolic Critical Depth
Global Vel Dist= 0 , 0 , 0
Global Log Level= 0
CheckData=True
Encroach Param=-1 ,0,0, 0
Mapping Interval=1HOUR
Computation Time Step Use Courant=        0
Computation Time Step Use Time Series=    0
Computation Time Step Count To Double=0
Computation Time Step Max Doubling=0
Computation Time Step Max Halving=0
Computation Time Step Residence Courant=0
Run HTab= 0
Run UNet= 0
Run Sediment= 0
Run PostProcess= 0
Run WQNet= 0
Run RASMapper= 0
UNET Theta= 0
UNET Theta Warmup= 0
UNET ZTol= 0
UNET ZSATol= 0
UNET MxIter= 0
UNET Max Iter WO Improvement= 0
UNET MaxInSteps= 0
UNET DtIC= 0
UNET DtMin= 0
UNET MaxCRTS= 0
UNET WFStab= 0
UNET SFStab= 0
UNET WFX= 1
UNET SFX= 1
UNET 1D Methodology=Finite Difference
UNET DSS MLevel= 1
UNET Pardiso=0
UNET DZMax Abort= 0
UNET Use Existing IB Tables= 0
UNET Froude Reduction=False
UNET Froude Limit= 0
UNET Froude Power= 0
UNET D1 Cores= 0
UNET D2 Coriolis=0
UNET D2 Cores= 0
UNET D2 Theta= 1
UNET D2 Theta Warmup= 1
UNET D2 Z Tol= 0.01
UNET D2 Volume Tol= 0.01
UNET D2 Max Iterations= 20
UNET D2 Equation= 0
UNET D2 RampUpFraction=0.1
UNET D2 TimeSlices= 1
UNET D2 BCVolumeCheck=0
UNET D1D2 MaxIter= 0
UNET D1D2 ZTol=0.01
UNET D1D2 QTol=0.1
UNET D1D2 MinQTol=1
Write IC File= 0
Write IC File at Fixed DateTime=0
Write IC File at Sim End=0
Echo Input=False
Echo Parameters=False
Echo Output=False
Write Detailed= 0
HDF Write Warmup=0
HDF Write Time Slices=0
HDF Flush=0
HDF Face Node Velocities=0
HDF Compression= 1
HDF Chunk Size= 1
HDF Spatial Parts= 1
HDF Use Max Rows=0
HDF Fixed Rows= 1
Calibration Method= 0
Calibration Iterations= 20
Calibration Max Change=0.05
Calibration Tolerance=0.2
Calibration Maximum=1.5
Calibration Minimum=0.5
Calibration Optimization Method= 1
WQ AD Non Conservative
WQ ULTIMATE=-1
WQ Max Comp Step=1HOUR
WQ Output Interval=15MIN
WQ Output Selected Increments= 0
WQ Output face flow=0
WQ Output face velocity=0
WQ Output face area=0
WQ Output face dispersion=0
WQ Output cell volume=0
WQ Output cell surface area=0
WQ Output cell continuity=0
WQ Output cumulative cell continuity=0
WQ Output face conc=0
WQ Output face dconc_dx=0
WQ Output face courant=0
WQ Output face peclet=0
WQ Output face adv mass=0
WQ Output face disp mass=0
WQ Output cell mass=0
WQ Output cell source sink temp=0
WQ Output nsm pathways=0
WQ Output nsm derived pathways=0
WQ Output MaxMinRange=-1
WQ Daily Max Min Mean=-1
WQ Daily Range=0
WQ Daily Time=0
WQ Create Restart=0
WQ Fixed Restart=0
WQ System Summary=0
WQ Write To DSS=0
WQ Use Fixed Temperature=0
Sorting and Armoring Iterations= 10
XS Update Threshold= 0.02
Bed Roughness Predictor= 0
Hydraulics Update Threshold= 0.02
Energy Slope Method= 1
Volume Change Method= 1
Sediment Retention Method= 0
XS Weighting Method= 0
Number of US Weighted Cross Sections= 1
Number of DS Weighted Cross Sections= 1
Upstream XS Weight=0
Main XS Weight=1
Downstream XS Weight=0
Number of DS XS's Weighted with US Boundary= 1
Upstream Boundary Weight= 1
Weight of XSs Associated with US Boundary= 0
Number of US XS's Weighted with DS Boundary= 1
Downstream Boundary Weight= 0.5
Weight of XSs Associated with DS Boundary= 0.5
Percentile Method= 0
Sediment Output Level= 3
Mass or Volume Output= 0
Output Increment Type= 1
Profile and TS Output Increment= 1
XS Output Flag= 0
XS Output Increment= 10
Write Gradation File= 0
Read Gradation Hotstart= 0
Write HDF5 File= 1
Write Binary Output= 1
Write DSS Sediment File= 0
SV Curve= 0
Specific Gage Flag= 0

--- BRDSHWCK2_A.f01 (steady flow) ---

Flow Title=Flows
Program Version=5.07
Number of Profiles= 6
Profile Names=01pct,10pct,04pct,02pct,0_2pct,01plus
River Rch & RM=BRDSHWCK2_A,Main            ,8941
     214     109     147     179     304     316
River Rch & RM=BRDSHWCK2_A,Main            ,8433
     536     283     376     454     750     793
River Rch & RM=BRDSHWCK2_A,Main            ,6198
     634     337     447     538     884     938
River Rch & RM=BRDSHWCK2_A,Main            ,2995
     854     458     605     726    1184    1263
River Rch & RM=BRDSHWCK2_A,Main            ,1178
    1753     968    1260    1499    2398    2593
River Rch & RM=BRDSHWCK2_A,Main            ,1
    1947    1079    1402    1666    2658    2880
Boundary for River Rch & Prof#=BRDSHWCK2_A,Main            , 1
Up Type= 0
Dn Type= 1
Dn Known WS=1596.6
Boundary for River Rch & Prof#=BRDSHWCK2_A,Main            , 2
Up Type= 0
Dn Type= 1
Dn Known WS=1594.5
Boundary for River Rch & Prof#=BRDSHWCK2_A,Main            , 3
Up Type= 0
Dn Type= 1
Dn Known WS=1595.3
Boundary for River Rch & Prof#=BRDSHWCK2_A,Main            , 4
Up Type= 0
Dn Type= 1
Dn Known WS=1595.9
Boundary for River Rch & Prof#=BRDSHWCK2_A,Main            , 5
Up Type= 0
Dn Type= 1
Dn Known WS=1597
Boundary for River Rch & Prof#=BRDSHWCK2_A,Main            , 6
Up Type= 0
Dn Type= 1
Dn Known WS=1597.2
DSS Import GetInterval= 0
DSS Import GetPeak= 0
DSS Import FillOption= 0

--- BRDSHWCK2_A.g01 (geometry) ---

Geom Title=Geometry
Program Version=5.07

River Reach=BRDSHWCK2_A     ,Main
Reach XY= 30
2030849.80160647204768.6648215522030791.66500002204598.087000009
     2030657.637 204566.83599999     2030527.776204636.974999971
2030315.27599999204451.558999989     2030181.249 204451.55900001
2029915.97100002204318.224999964     2029663.193 204377.25299999
     2029586.804204273.0870000512029268.74799999204155.725000019
     2029031.249203930.7250000212028782.63800001203901.559000035
     2028677.082203768.2250000052028382.42200001 203672.59600004
2028334.72100001203540.4479999742028097.73308542 203492.56162374
2028006.24899999203308.5029999992027479.16500001203169.614000023
      2027392.75202962.9330000132026795.13799999202954.336999982
     2026621.526202841.8370000412026622.99900002202737.111000001
2026402.08200001202708.5030000142026278.47100002202548.086000039
2026293.74900002202371.002999998     2026195.137202182.113999987
2026409.02600004201431.4199999932026406.74800002200817.599000032
      2026579.86200332.8090000072026302.64828396199661.659839144

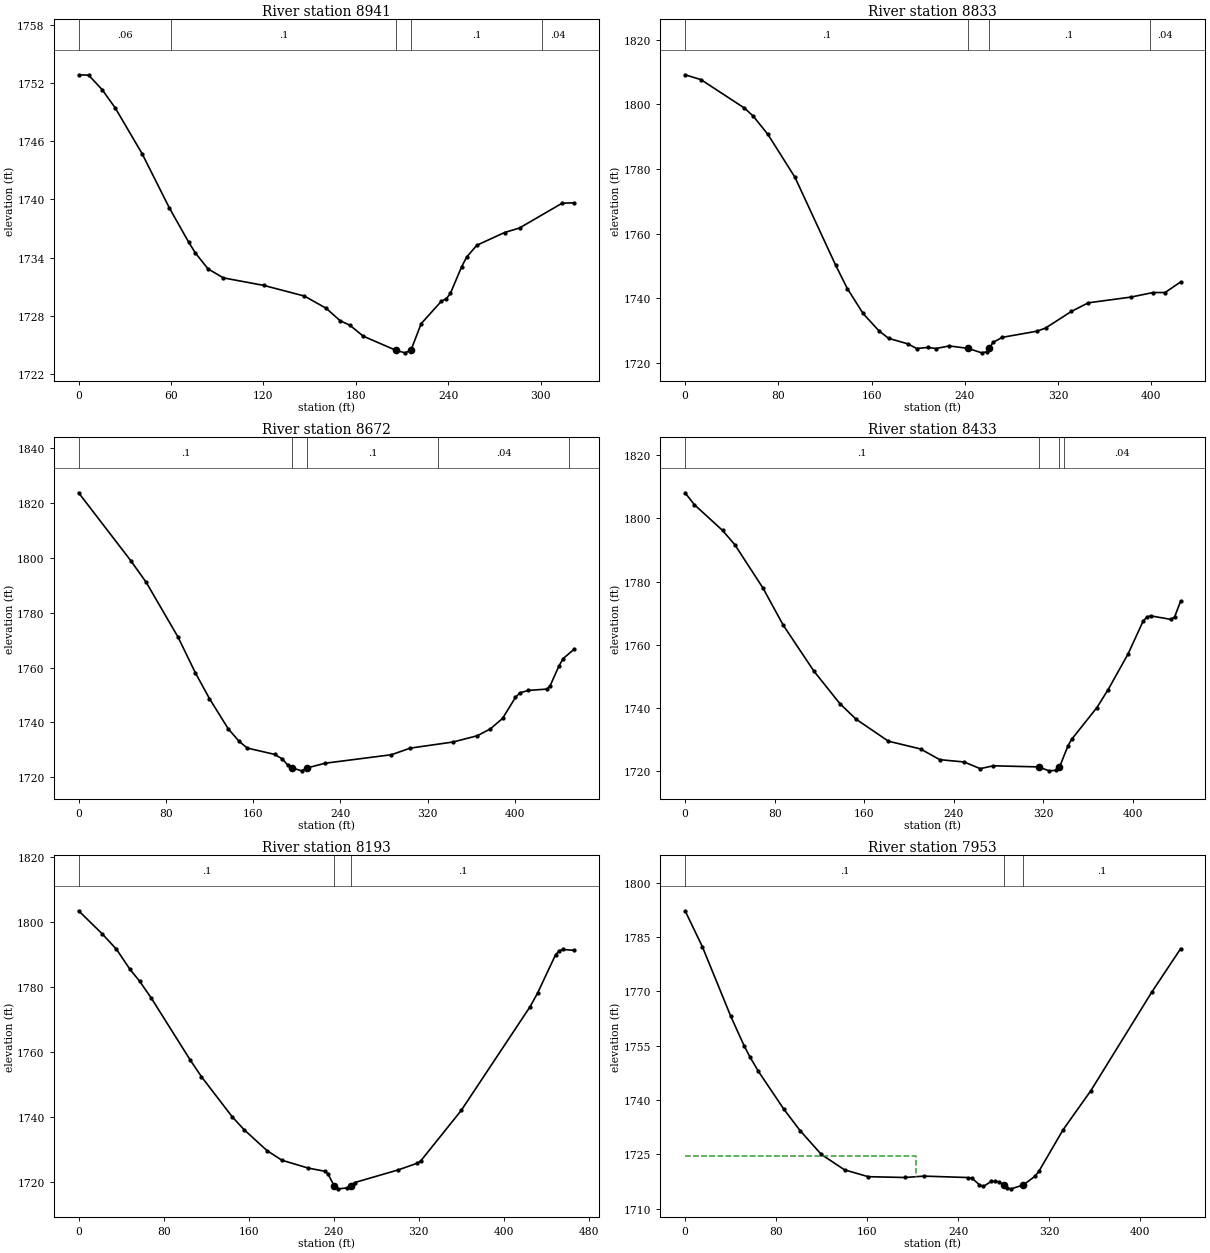
Type RM Length L Ch R = 1 ,8941    ,112.8,108.3,85.9
XS GIS Cut Line= 4
2031035.27056566 204698.416296052030972.77056569204752.235740513
2030794.81917679 204768.728796052030752.28445458 204811.84222199
#Sta/Elev= 30
       0 1752.87     6.5 1752.83    15.2 1751.35    23.8 1749.44    41.2 1744.73
      59  1739.1    71.5 1735.58    75.8 1734.48      84 1732.84    93.9 1731.91
   120.2 1731.13   146.6 1730.03   160.7 1728.77   169.7  1727.5   176.2 1727.01
   184.8 1725.89   205.9 1724.44   211.9 1724.17   215.8 1724.45   222.4 1727.18
   235.5 1729.49   238.8 1729.77   241.4 1730.31   248.7 1733.06     252 1734.07
   258.6 1735.28   276.6 1736.59   286.3 1737.06   313.9 1739.61321.7568 1739.66
#Mann= 5 ,-1 , 0
       0     .06       0      60      .1       0   205.9    .045       0
   215.8      .1       0  301.19     .04       0
Bank Sta=205.9,215.8
XS Rating Curve= 0 ,0
Exp/Cntr(USF)=0,0
Exp/Cntr=0.3,0.1

Type RM Length L Ch R = 1 ,8833    ,163.2,160.7,153.8
XS GIS Cut Line= 4
2030983.03317328204497.7810422912030874.07593336204614.520942209
2030771.34482143204707.9128621422030715.30966947204821.539698062
#Sta/Elev= 30
       0 1809.12    13.6 1807.62    50.9 1798.84    58.5 1796.33    71.1 1790.67
    94.3 1777.42   129.1 1750.34   139.2 1743.05   152.7 1735.37   166.2 1730.03
   174.6 1727.68   191.1 1725.97   198.7 1724.53     208 1724.85   215.5 1724.53
   226.6 1725.33   242.9 1724.56   254.5 1723.19   258.9 1723.52  260.831724.547
   264.3 1726.45   272.2 1727.98   302.1 1729.89   309.4 1730.87   331.4 1735.98
     346 1738.65   382.6 1740.42   401.5 1741.83   411.8 1741.82   425.2  1745.1
#Mann= 4 ,-1 , 0
       0      .1       0   242.9    .045       0  260.83      .1       0
  398.52     .04       0
Bank Sta=242.9,260.83
XS Rating Curve= 0 ,0
Exp/Cntr(USF)=0,0
Exp/Cntr=0.3,0.1

Type RM Length L Ch R = 1 ,8672    ,234.6,239.5,238.6
XS GIS Cut Line= 4
 2030814.9277174 204401.276058362030752.66643745204511.789830281
 2030684.1790295204670.5560941692030597.01323756204798.191718079
#Sta/Elev= 30
       0 1823.77    47.7 1799.06    61.9 1791.13      91 1771.22   107.1 1758.04
   119.9 1748.72   137.1 1737.71   147.1  1733.1   154.6 1730.65   179.6 1728.35
   186.7 1726.69   192.1 1724.29  195.93 1723.39   204.4 1722.34  209.371723.391
     226 1725.12   286.8 1728.22   304.1 1730.63   343.3 1732.86   365.5 1735.14
   377.3 1737.61   388.6 1741.44   400.5 1749.15   404.5 1750.79   412.4 1751.68
   429.3 1752.16   432.3 1753.42   440.3 1760.54   444.2  1763.3   454.3 1766.71
#Mann= 5 ,-1 , 0
       0      .1       0  195.93    .045       0  209.37      .1       0
  329.75     .04       0  449.75      .1       0
Bank Sta=195.93,209.37
XS Rating Curve= 0 ,0
Exp/Cntr(USF)=0,0
Exp/Cntr=0.3,0.1

Type RM Length L Ch R = 1 ,8433    ,238.6,239.7,239.8
XS GIS Cut Line= 4
2030642.15266553 204329.675586412030567.43912958204491.554914296
2030492.72559363204665.8864981722030466.26454965204735.930438123
#Sta/Elev= 30
       0 1808.08     8.2 1804.35    33.5 1796.16    44.5 1791.62    69.6 1777.93
    87.7 1766.19     115  1751.7   138.3 1741.38   152.7 1736.47   181.6  1729.5
   210.4 1727.03   227.5 1723.65   249.4 1722.91   263.7  1720.8   275.3  1721.7
   315.8 1721.36   325.3 1720.11   331.5 1720.28   334.5 1721.27   342.2 1728.07
   345.3 1730.03     368 1740.14     378 1745.81   395.8 1757.07   409.3 1767.49
   412.8 1768.84   416.3 1769.12     434 1768.03   437.4 1768.79   442.8 1773.82
#Mann= 4 ,-1 , 0
       0      .1       0   315.8    .045       0   334.5      .1       0
  338.29     .04       0
Bank Sta=315.8,334.5
XS Rating Curve= 0 ,0
Exp/Cntr(USF)=0,0
Exp/Cntr=0.3,0.1

Type RM Length L Ch R = 1 ,8193    ,240,240,239.9
XS GIS Cut Line= 4
2030446.02963367204239.3967304742030374.42916172204388.823802369
2030312.16788176204542.9204702592030274.81111379204672.112626168
#Sta/Elev= 30
       0 1803.46    22.1  1796.4    35.6 1791.64    48.4 1785.43    57.4 1781.83
    68.3 1776.68     105 1757.63   115.6 1752.48   144.7 1740.11   155.6 1736.25
   177.2  1729.8   191.3 1726.82   216.1 1724.41     232 1723.41   234.5 1722.71
  240.38 1719.02   244.4 1718.03   252.2 1718.28  255.931719.019   259.7 1719.95
     301 1723.87   318.7  1725.9   322.2 1726.69   360.1 1742.12     425 1774.04
   431.9 1778.14   448.9 1789.96   452.3 1791.17   455.8 1791.57   466.4  1791.3
#Mann= 3 ,-1 , 0
       0      .1       0  240.38    .045       0  255.93      .1       0
Bank Sta=240.38,255.93
XS Rating Curve= 0 ,0
Exp/Cntr(USF)=0,0
Exp/Cntr=0.3,0.1

Type RM Length L Ch R = 1 ,7953    ,259.5,251.8,244.1
XS GIS Cut Line= 4
2030225.00208982204146.0048105412030173.63653386204264.301242457
2030106.70565791204449.5285503262030064.67929394204550.703130254
#Sta/Elev= 30
       0 1792.22    15.2 1782.29    40.2 1763.07    51.8 1755.03    56.8 1752.01
    64.3 1747.99    86.7 1737.53     101 1731.61   119.7 1725.02   140.1 1720.76
     161 1718.87   193.2 1718.65   209.9 1719.03   248.2 1718.64   252.2 1718.44
   258.7 1716.63   262.2 1716.19   269.2  1717.6   272.7 1717.66   276.2 1717.39
   280.3 1716.45   283.1 1715.69   286.6 1715.52  297.23 1716.59   307.5    1719
     311  1720.4   332.1 1731.77   356.6 1742.61   410.2 1769.82   435.5 1781.77
#Mann= 3 ,-1 , 0
       0      .1       0   280.3    .045       0  297.23      .1       0
#XS Ineff= 2 , 0
          202.72 1724.51
Permanent Ineff=
       F       F
Bank Sta=280.3,297.23
XS Rating Curve= 0 ,0
Exp/Cntr(USF)=0,0
Exp/Cntr=0.3,0.1

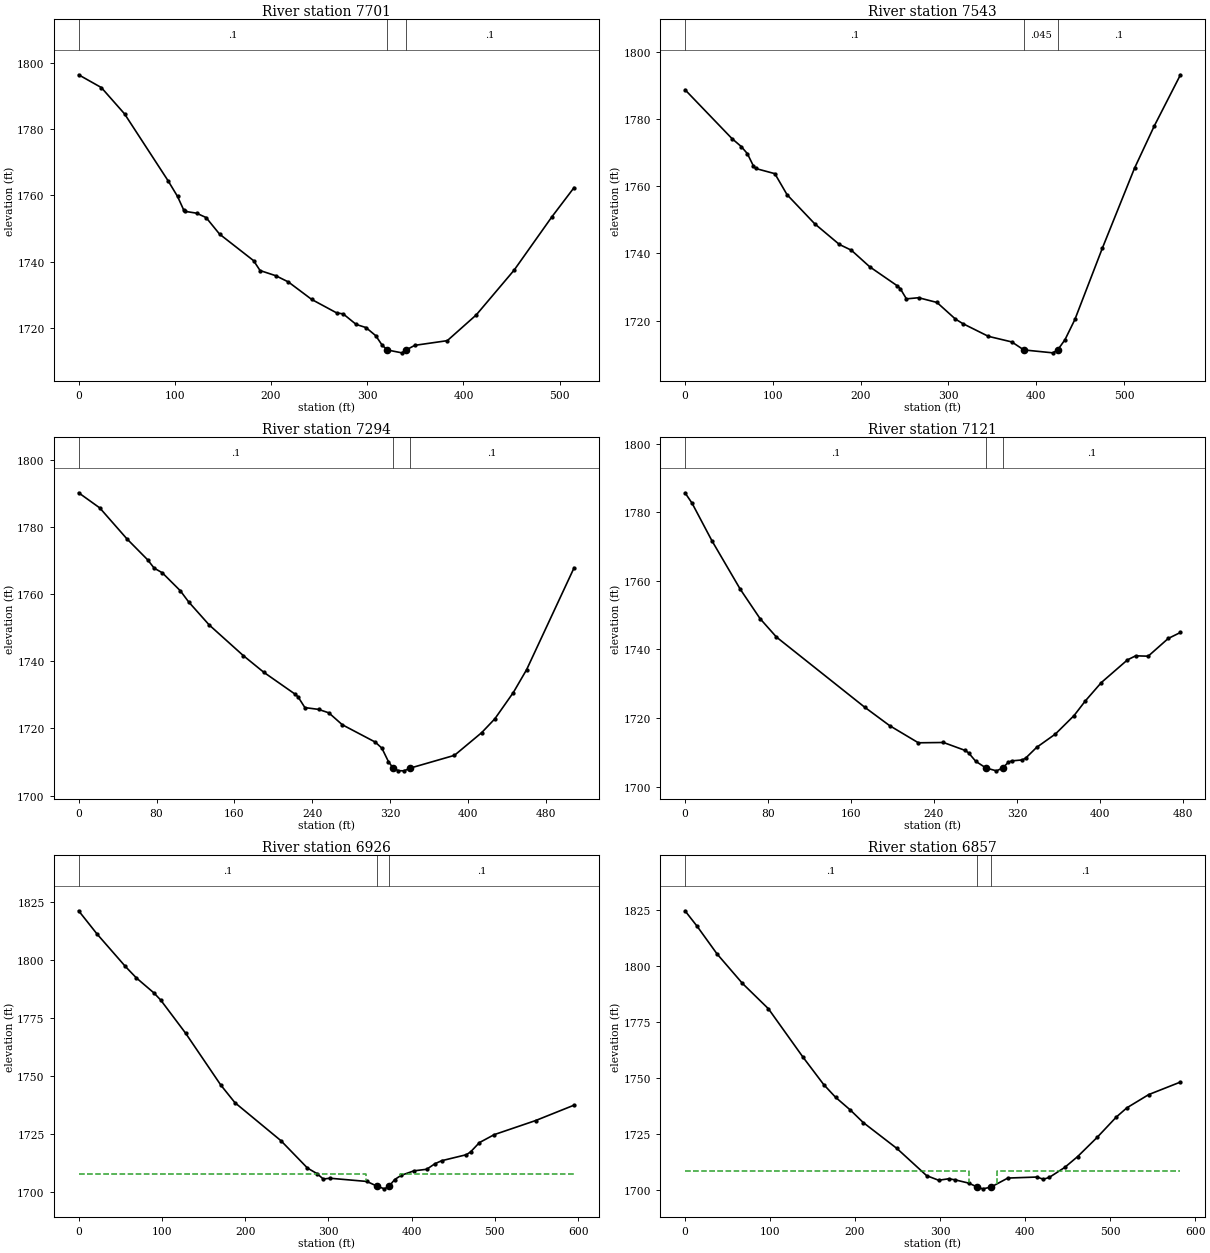
Type RM Length L Ch R = 1 ,7701    ,152,158,160.1
XS GIS Cut Line= 4
2029907.46956205203988.7950786522029882.56505006204234.727134478
2029919.92181804204382.5976743732029915.25222204204497.781042291
#Sta/Elev= 30
       0 1796.38    23.6 1792.53    47.7 1784.61    92.9 1764.47   102.8 1759.71
   109.4 1755.51   110.5 1755.22   122.6 1754.66   132.5 1753.34   146.5 1748.35
   181.9 1740.34   188.6 1737.37     205  1735.8     218 1733.93   242.3 1728.65
   268.2  1724.6     275  1724.3   288.5 1721.12   298.6 1720.19   308.8 1717.74
   315.6 1714.83     3211713.418   335.9 1712.56  340.381713.418   349.4 1714.82
   383.2 1716.23   413.3 1723.99   452.7  1737.5   492.1 1753.63     515 1762.38
#Mann= 3 ,-1 , 0
       0      .1       0     321    .045       0  340.38      .1       0
Bank Sta=321,340.38
XS Rating Curve= 0 ,0
Exp/Cntr(USF)=0,0
Exp/Cntr=0.3,0.1

Type RM Length L Ch R = 1 ,7543    ,225.3,249.4,254.8
XS GIS Cut Line= 4
2029862.33013408204001.2473346432029751.81636216204310.997202424
2029776.72087414204451.0850823242029762.71208615204542.920470259
#Sta/Elev= 30
       0 1788.68    53.5 1774.14      64 1771.79      71 1769.67    77.9    1766
    80.5 1765.25   102.3 1763.71   116.2 1757.46   147.6 1748.83   175.7 1742.67
   189.4 1740.95   210.3 1736.02   241.6 1730.38   245.1 1729.51   252.1 1726.48
     266 1726.82   286.9 1725.41   307.8 1720.49   316.1 1719.15   345.4 1715.34
   372.1 1713.67  385.761711.296   418.7 1710.43   424.31711.295   432.6 1714.32
   443.9 1720.35   475.3 1741.64   511.8 1765.34   534.2 1777.85   564.1 1793.12
#Mann= 3 ,-1 , 0
       0      .1       0  385.76    .045       0   424.3      .1       0
Bank Sta=385.76,424.3
XS Rating Curve= 0 ,0
Exp/Cntr(USF)=0,0
Exp/Cntr=0.3,0.1

Type RM Length L Ch R = 1 ,7294    ,171.7,172.5,173.2
XS GIS Cut Line= 4
 2029689.5550822203959.2209706732029594.60663027204208.266090497
 2029555.6933303204360.8062263882029535.45841431 204443.30242233
#Sta/Elev= 30
       0 1790.11    21.7 1785.61    49.6  1776.4    70.9 1770.16    77.6 1767.68
    85.9 1766.31   104.4 1760.97     113 1757.64   134.1 1750.78   169.2 1741.64
   190.2 1736.69   221.8 1730.29   225.3 1729.41   232.4 1726.18   246.4 1725.65
     257 1724.62   270.8 1721.08   304.7 1715.91   311.5  1714.1   318.2 1710.11
  322.991708.195   328.4 1707.41   334.2 1707.36  340.811708.194     386 1711.97
     414 1718.73   427.5 1722.84   446.5 1730.67   460.1 1737.45   508.9 1767.79
#Mann= 3 ,-1 , 0
       0      .1       0  322.99    .045       0  340.81      .1       0
Bank Sta=322.99,340.81
XS Rating Curve= 0 ,0
Exp/Cntr(USF)=0,0
Exp/Cntr=0.3,0.1

Type RM Length L Ch R = 1 ,7121    ,192.8,195.7,199
XS GIS Cut Line= 4
2029543.49987326 203966.355589842029446.84651764204130.373405436
2029394.12650549204288.533441904 2029335.5487142204393.973466216
#Sta/Elev= 30
       0 1785.66     6.8 1782.63    25.9 1771.71    53.3 1757.55    72.4 1748.98
    88.2 1743.61   173.3 1723.17   197.3 1717.81     225 1712.81   249.2  1712.9
     270  1710.6   273.4 1709.89   280.3 1707.42   290.2 1705.47   300.3 1704.64
  306.351705.469   311.5 1707.08   314.9 1707.54   325.3 1707.82   328.7 1708.42
     339 1711.47   357.1 1715.36   375.1 1720.74     386 1725.02   401.4 1730.36
   426.6 1736.97   434.5 1738.15   446.6 1738.05   465.9 1743.21   477.7 1744.96
#Mann= 3 ,-1 , 0
       0      .1       0   290.2    .045       0  306.35      .1       0
Bank Sta=290.2,306.35
XS Rating Curve= 0 ,0
Exp/Cntr(USF)=0,0
Exp/Cntr=0.5,0.3

Type RM Length L Ch R = 1 ,6926    ,69.1,69,69.2
XS GIS Cut Line= 4
2029466.97100636203840.9245387572029309.76127447204032.377974621
2029222.59548253204169.3527905242029152.55154258204340.571310403
#Sta/Elev= 30
       0 1821.18    22.2 1811.14    56.2 1797.18    69.3 1792.28    90.4 1785.81
    98.6 1782.72   128.4  1768.5   170.8 1746.09   187.8  1738.5     243 1722.15
   274.9 1710.35   286.2 1707.99   293.9 1705.63   301.7 1705.98   346.2 1704.59
  358.451702.551   367.3 1701.41   372.91702.551   379.5 1705.37   387.3 1707.21
   402.8 1709.17     418 1709.83     428 1712.23   436.1 1713.53   465.8 1716.12
   470.8 1717.33   481.4 1721.33   499.2 1724.76   548.8 1730.81   595.1 1737.46
#Mann= 3 ,-1 , 0
       0      .1       0  358.45    .045       0   372.9      .1       0
#XS Ineff= 2 , 0
          345.54 1707.85  385.89         1707.72
Permanent Ineff=
       F       F
Bank Sta=358.45,372.9
XS Rating Curve= 0 ,0
Exp/Cntr(USF)=0,0
Exp/Cntr=0.5,0.3

Type RM Length L Ch R = 1 ,6857    ,134.4,135.5,132.9
XS GIS Cut Line= 4
2029417.16198239203812.9069627772029228.82161053204035.491038619
2029157.22113858204142.8917465432029098.07292262204293.875350436
#Sta/Elev= 30
       0 1824.49    14.2  1817.6    37.7 1805.23    67.6 1792.06    98.1 1780.77
   138.7 1759.21   163.1 1746.95   177.1 1741.25   194.6 1735.52   209.6 1729.99
   249.3 1718.39   284.2 1706.27   298.3 1704.22   310.1 1704.86   317.2 1704.44
   333.8 1702.93  343.981701.143   350.3 1700.38  359.821701.144   379.7 1705.19
   414.2 1705.65   421.4 1704.66   428.4 1705.46   446.7 1709.95   461.9  1714.8
   484.8 1723.35   507.4 1732.45   519.8 1736.55   545.4 1742.44   582.8 1748.05
#Mann= 3 ,-1 , 0
       0      .1       0  343.98    .045       0  359.82      .1       0
#XS Ineff= 2 , 0
          333.52 1708.49  366.94         1708.38
Permanent Ineff=
       F       F
Bank Sta=343.98,359.82
XS Rating Curve= 0 ,0
Exp/Cntr(USF)=0,0
Exp/Cntr=0.5,0.3

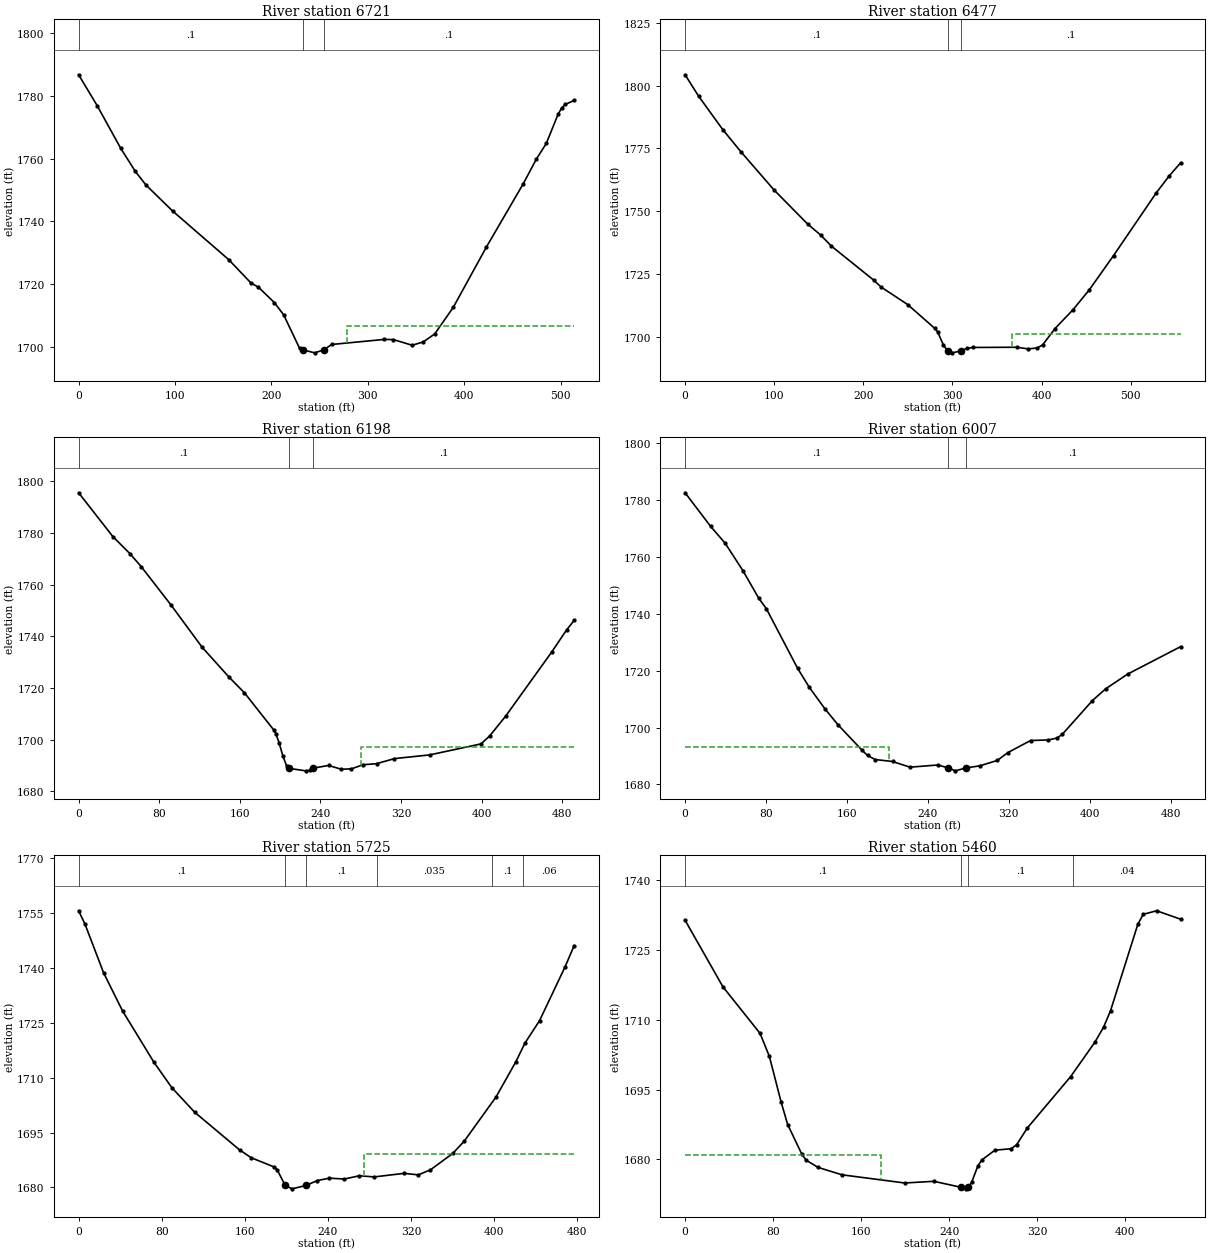
Type RM Length L Ch R = 1 ,6721    ,249.6,244.2,234.9
XS GIS Cut Line= 4
2029235.96646902203781.8355472942029159.81534035203904.848908991
2029030.94419952204106.942288922 2028975.2952978204224.097871491
#Sta/Elev= 30
       0  1786.8    19.2 1776.96    43.7  1763.3    58.8 1755.95    69.9 1751.58
    97.4 1743.32   155.7 1727.77   178.7 1720.34   186.6 1718.95   203.2 1714.01
   212.7 1710.14   229.3  1699.4  232.791698.945   244.9    1698  254.261698.945
   262.6 1700.67   317.2 1702.29   326.6 1702.23   346.1 1700.42   357.6  1701.5
   369.4 1704.03   388.7 1712.54   423.1 1731.82   461.2 1751.95   474.8 1759.84
   485.2 1764.88   497.5 1774.27   501.2 1776.21   504.8 1777.31   514.1 1778.63
#Mann= 3 ,-1 , 0
       0      .1       0  232.79    .045       0  254.26      .1       0
#XS Ineff= 2 , 0
                          278.51         1706.59
Permanent Ineff=
       F       F
Bank Sta=232.79,254.26
XS Rating Curve= 0 ,0
Exp/Cntr(USF)=0,0
Exp/Cntr=0.3,0.1

Type RM Length L Ch R = 1 ,6477    ,274.6,279.4,286.4
XS GIS Cut Line= 5
2029013.37086214203629.5332899552028890.35750044203852.128896835
2028887.42861088203937.0666941982028877.44183997204029.135003525
2028826.55095456204142.365391593
#Sta/Elev= 30
       01804.315  15.1271795.821  42.2591782.507  62.6081773.683  99.9711758.404
 137.4561744.926  152.451740.416 163.9291736.195 211.8331722.525 219.9221719.829
  249.911712.825 280.0041703.412 283.2871702.029 289.8521696.776  294.551694.451
   299.71693.641  309.961694.418 316.114 1695.42  322.681695.781 372.0931695.868
 385.2941695.208 395.2121695.595 401.1661696.793 414.9941703.273 435.0531710.714
 453.4361718.654 480.7341732.333 528.5751757.252 542.9631763.947 556.0631769.295
#Mann= 3 ,-1 , 0
       0      .1       0  294.55    .045       0  309.96      .1       0
#XS Ineff= 2 , 0
                          367.05         1701.14
Permanent Ineff=
       F       F
Bank Sta=294.55,309.96
XS Rating Curve= 0 ,0
Exp/Cntr(USF)=0,0
Exp/Cntr=0.3,0.1

Type RM Length L Ch R = 1 ,6198    ,194.8,190.2,187.9
XS GIS Cut Line= 4
2028817.13526134203588.5288360562028711.69523702203720.328866446
2028620.89966053203878.4889029132028571.10853794204010.288933303
#Sta/Elev= 30
       0  1795.5      34 1778.55    51.1 1771.88    62.1 1766.95    91.5 1752.19
   122.7 1735.68   149.2 1724.22   164.6 1718.11   193.5 1703.83   195.9 1702.24
     199 1698.78   202.8 1693.65   206.6 1689.69  209.121688.848   225.5  1687.9
   229.3 1688.04   233.1 1688.97   248.2 1689.98   260.8 1688.51   270.9 1688.69
   282.4 1690.26   295.8 1690.67   313.6 1692.64   348.6 1694.07   399.5 1698.32
   408.2 1701.44   424.1 1709.13   469.7 1733.88   484.5 1742.44     492 1746.13
#Mann= 3 ,-1 , 0
       0      .1       0  209.12    .045       0   233.1      .1       0
#XS Ineff= 2 , 0
                             280          1697.2
Permanent Ineff=
       F       F
Bank Sta=209.12,233.1
XS Rating Curve= 0 ,0
Exp/Cntr(USF)=0,0
Exp/Cntr=0.3,0.1

Type RM Length L Ch R = 1 ,6007    ,277.3,282.4,277.3
XS GIS Cut Line= 4
2028617.97077097203471.3732534872028538.89075274203600.244394313
2028483.24185102203770.1199890372028363.15737888203875.560013349
#Sta/Elev= 30
       0 1782.65    25.3 1770.79    39.6 1764.89    57.3 1755.14    72.7 1745.59
    80.4 1741.79   111.1 1720.91   122.7  1714.2   138.1 1706.64   151.2 1700.94
   175.1 1691.94   180.3 1690.18   187.8 1688.74     205 1688.05   222.3 1686.05
   249.9 1686.82  260.221685.774   267.2 1684.76  277.371685.773   291.4 1686.53
   308.6 1688.42     319 1691.18   341.5 1695.44     359 1695.63   367.7 1696.33
   372.9 1697.64   402.6  1709.5   415.7 1713.64   437.6 1718.86   489.8 1728.48
#Mann= 3 ,-1 , 0
       0      .1       0  260.22    .045       0  277.37      .1       0
#XS Ineff= 2 , 0
          201.65 1693.09
Permanent Ineff=
       F       F
Bank Sta=260.22,277.37
XS Rating Curve= 0 ,0
Exp/Cntr(USF)=0,0
Exp/Cntr=0.3,0.1

Type RM Length L Ch R = 1 ,5725    ,261.1,265.2,261.7
XS GIS Cut Line= 4
2028421.73517017203354.2176709182028366.08626845203468.444363923
2028266.50402326203688.1110812392028210.85512154203781.835547294
#Sta/Elev= 30
       0 1755.68     6.1 1752.05      24 1738.74    42.3 1728.29    72.4  1714.3
    89.7 1707.32   111.6 1700.62     155 1690.28   166.3 1688.12   188.3 1685.61
   191.1 1684.88  198.921680.564   205.5 1679.63  219.081680.564   229.9  1681.9
   241.5 1682.55   255.9 1682.31   270.3 1683.21   284.7 1682.89   313.5 1683.87
   327.1 1683.45   338.8 1684.83   360.4 1689.34   371.4 1692.69   401.9 1704.74
     421 1714.36   429.8 1719.49   443.9 1725.65   468.4 1740.33   477.2 1746.16
#Mann= 6 ,-1 , 0
       0      .1       0  198.92    .045       0  219.08      .1       0
  287.06    .035       0  398.25      .1       0  428.25     .06       0
#XS Ineff= 2 , 0
                          275.11         1689.15
Permanent Ineff=
       F       F
Bank Sta=198.92,219.08
XS Rating Curve= 0 ,0
Exp/Cntr(USF)=0,0
Exp/Cntr=0.3,0.1

Type RM Length L Ch R = 1 ,5460    ,274.3,278.4,273.8
XS GIS Cut Line= 4
2028213.78401111203263.4220944282028146.41955113 203348.35989179
2028049.76619551203550.4532717212027997.04618336203655.893296033
#Sta/Elev= 30
       0 1731.43    34.4 1717.11    68.1 1707.11    76.6 1702.15    87.2 1692.39
    93.2 1687.51   105.8 1681.26   109.8 1679.88   120.7  1678.3   142.5  1676.7
   199.5 1674.94   226.1  1675.3   250.5 1674.02   255.2 1673.68   257.5 1674.04
   260.4 1675.09   266.1 1678.65   269.8 1679.92   281.5 1681.99   296.3 1682.31
   301.2 1683.15     311 1686.77   350.3  1697.8   372.3 1705.18   380.3 1708.45
   386.6 1711.98   411.4 1730.57   416.3 1732.71   428.5 1733.47   450.3 1731.66
#Mann= 4 ,-1 , 0
       0      .1       0   250.5    .045       0   257.5      .1       0
  352.43     .04       0
#XS Ineff= 2 , 0
          177.65 1680.98
Permanent Ineff=
       F       F
Bank Sta=250.5,257.5
XS Rating Curve= 0 ,0
Exp/Cntr(USF)=0,0
Exp/Cntr=0.3,0.1

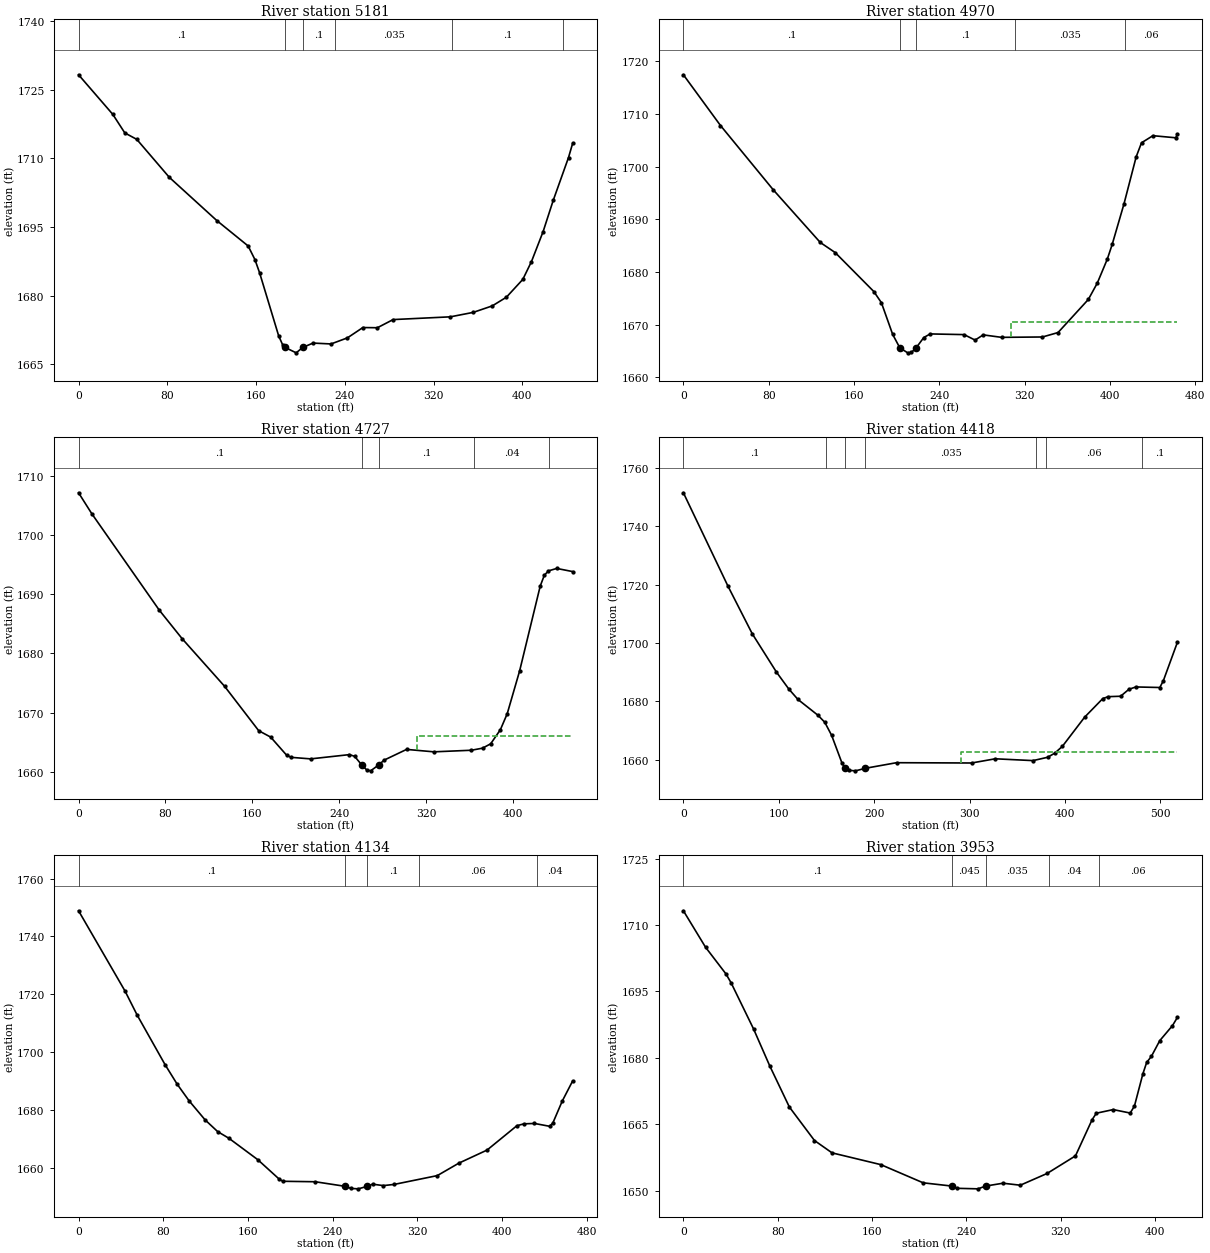
Type RM Length L Ch R = 1 ,5181    ,209.5,211,211.3
XS GIS Cut Line= 4
2027997.04618336203108.1909475242027938.46839207 203237.06208835
2027885.74837992 203404.008793512027847.67281558203527.022155207
#Sta/Elev= 30
       0 1728.23    30.9 1719.58    41.7 1715.54    52.5 1714.13    81.8 1705.85
   124.6 1696.42   152.9 1690.86     159 1687.89   163.2 1685.02   180.4 1671.25
   183.9 1669.34  186.281668.709   196.2 1667.54  202.031668.708   211.4 1669.67
   227.6 1669.48   242.4 1670.81   256.3 1673.06   269.4 1673.02   283.6  1674.8
   335.2  1675.4   355.8 1676.37     373 1677.79   385.7 1679.68   400.5 1683.57
   408.3 1687.45   418.8    1694   427.9  1700.8   441.7 1710.17   445.4 1713.24
#Mann= 6 ,-1 , 0
       0      .1       0  186.28    .045       0  202.03      .1       0
  231.56    .035       0  336.63      .1       0  436.63     .06       0
Bank Sta=186.28,202.03
XS Rating Curve= 0 ,0
Exp/Cntr(USF)=0,0
Exp/Cntr=0.3,0.1

Type RM Length L Ch R = 1 ,4970    ,242.1,243.6,245
XS GIS Cut Line= 4
2027812.52614081203037.8975979832027745.16168083203172.626517937
2027663.15277303203380.5776769962027628.00609826203462.586584794
#Sta/Elev= 30
       0 1717.44    34.8 1707.81    84.4 1695.58   128.4 1685.61   142.4 1683.69
   178.6  1676.3   185.7 1674.19   196.3 1668.16  202.981665.622   210.4 1664.66
   213.9 1664.74  218.341665.624   225.5 1667.57   231.5 1668.25   263.3 1668.12
   273.6 1667.08   281.2 1668.07   298.5  1667.6   336.8 1667.67   351.4 1668.51
   379.8 1674.79   388.2 1677.89   397.6 1682.44   402.2 1685.24   413.2 1692.89
   424.7 1701.87   429.7 1704.53   440.4 1705.88   461.8 1705.48   463.4 1706.15
#Mann= 5 ,-1 , 0
       0      .1       0  202.98    .045       0  218.34      .1       0
  310.63    .035       0  414.17     .06       0
#XS Ineff= 2 , 0
                          307.31         1670.59
Permanent Ineff=
       F       F
Bank Sta=202.98,218.34
XS Rating Curve= 0 ,0
Exp/Cntr(USF)=0,0
Exp/Cntr=0.3,0.1

Type RM Length L Ch R = 1 ,4727    ,309.7,309.1,305.2
XS GIS Cut Line= 4
2027613.36165044202938.3153527992027554.78385916203058.399824932
2027446.41494528 203272.208763122027405.41049138203342.502112662
#Sta/Elev= 30
       0 1707.13    12.2 1703.59    74.3  1687.3    95.3 1682.49   134.4 1674.44
   165.8 1666.94   176.8 1665.86   191.5  1662.8   195.6 1662.44   213.6 1662.18
   249.3  1662.9   254.1 1662.61  260.421661.199   265.1 1660.33   268.8 1660.16
  276.55  1661.2   281.1 1661.96   301.9 1663.78     327 1663.37   361.6 1663.64
   371.8 1663.99   379.3 1664.73   388.2  1667.1   394.5  1669.8   405.9 1677.02
   424.9 1691.38   428.7 1693.21   432.5 1693.94   440.1 1694.35   454.7 1693.82
#Mann= 5 ,-1 , 0
       0      .1       0  260.42    .045       0  276.55      .1       0
  363.61     .04       0  433.31     .06       0
#XS Ineff= 2 , 0
                           311.6         1665.98
Permanent Ineff=
       F       F
Bank Sta=260.42,276.55
XS Rating Curve= 0 ,0
Exp/Cntr(USF)=0,0
Exp/Cntr=0.3,0.1

Type RM Length L Ch R = 1 ,4418    ,285.2,283.5,280.2
XS GIS Cut Line= 4
2027411.26827051202788.9419850242027355.61936879202906.097567593
2027247.25045492203155.053180552 2027191.6015532203257.564315299
#Sta/Elev= 30
       0 1751.48    46.8 1719.41    72.2 1703.12    97.6 1689.96   110.5 1684.18
   120.1  1680.6   141.1 1675.17   148.2 1672.78   155.4 1668.29   166.1 1658.91
  169.541656.999   173.3  1656.3   180.4 1656.12  190.831656.999   223.4 1658.91
   302.1 1658.81   326.9 1660.25   366.5 1659.63   381.8 1660.77   389.3 1662.18
   397.3 1664.53   420.6 1674.52   439.6 1680.89   445.3 1681.56   458.3  1681.7
     467 1684.08   474.3 1684.89   499.4  1684.7   503.1 1687.01   517.9 1700.25
#Mann= 7 ,-1 , 0
       0      .1       0   149.7    .035       0  169.54    .045       0
  190.83    .035       0   369.7     .04       0   379.7     .06       0
  481.22      .1       0
#XS Ineff= 2 , 0
                           291.4         1662.59
Permanent Ineff=
       F       F
Bank Sta=169.54,190.83
XS Rating Curve= 0 ,0
Exp/Cntr(USF)=0,0
Exp/Cntr=0.3,0.1

Type RM Length L Ch R = 1 ,4134    ,178.5,181.1,184.6
XS GIS Cut Line= 4
2027162.31265755202727.4353041762027092.01930801202850.448665873
2027036.37040629203064.2576040612026980.72150457203152.124290987
#Sta/Elev= 30
       0 1748.87    43.9 1721.14    55.3 1712.88    81.7 1695.73    93.1    1689
   104.4 1683.24   119.5 1676.66   131.4  1672.6   142.1 1670.28   169.3  1662.9
   189.6 1656.16     193 1655.45   223.5 1655.29  251.531653.725   257.4 1652.98
   264.2 1652.84  272.861653.724   277.7 1654.45   287.9 1653.96   298.1 1654.37
   338.8 1657.41   359.1  1661.7   385.8 1666.23     414 1674.65   420.7 1675.29
   430.6 1675.42   444.9 1674.44   447.9 1675.55   456.8 1683.14   466.6 1690.08
#Mann= 5 ,-1 , 0
       0      .1       0  251.53    .045       0  272.86      .1       0
  321.68     .06       0  432.61     .04       0
Bank Sta=251.53,272.86
XS Rating Curve= 0 ,0
Exp/Cntr(USF)=0,0
Exp/Cntr=0.3,0.1

Type RM Length L Ch R = 1 ,3953    ,190.9,192.7,186
XS GIS Cut Line= 4
2027007.08151065202715.7197459192026925.07260285 202841.66199718
2026851.85036375203008.6087023412026816.70368898203087.688720575
#Sta/Elev= 30
       0 1713.22    18.8 1704.98      36 1698.99    40.4 1696.98    59.5 1686.53
    73.3 1678.14    89.9 1668.87   111.2  1661.3   126.1 1658.51   167.5 1655.85
   203.4 1651.74  227.61 1651.01     232  1650.5   249.9 1650.38  256.45 1651.01
   271.1 1651.65   285.8  1651.2   308.5 1653.85   332.6 1657.83   346.7    1666
   350.3 1667.47   364.6 1668.29     379 1667.51   382.6 1669.07   389.8 1676.39
     393 1678.95     397 1680.32   404.1 1683.87   414.9 1687.27   419.1 1689.14
#Mann= 5 ,-1 , 0
       0      .1       0  227.61    .045       0  256.45    .035       0
  310.29     .04       0  352.59     .06       0
Bank Sta=227.61,256.45
XS Rating Curve= 0 ,0
Exp/Cntr(USF)=0,0
Exp/Cntr=0.3,0.1

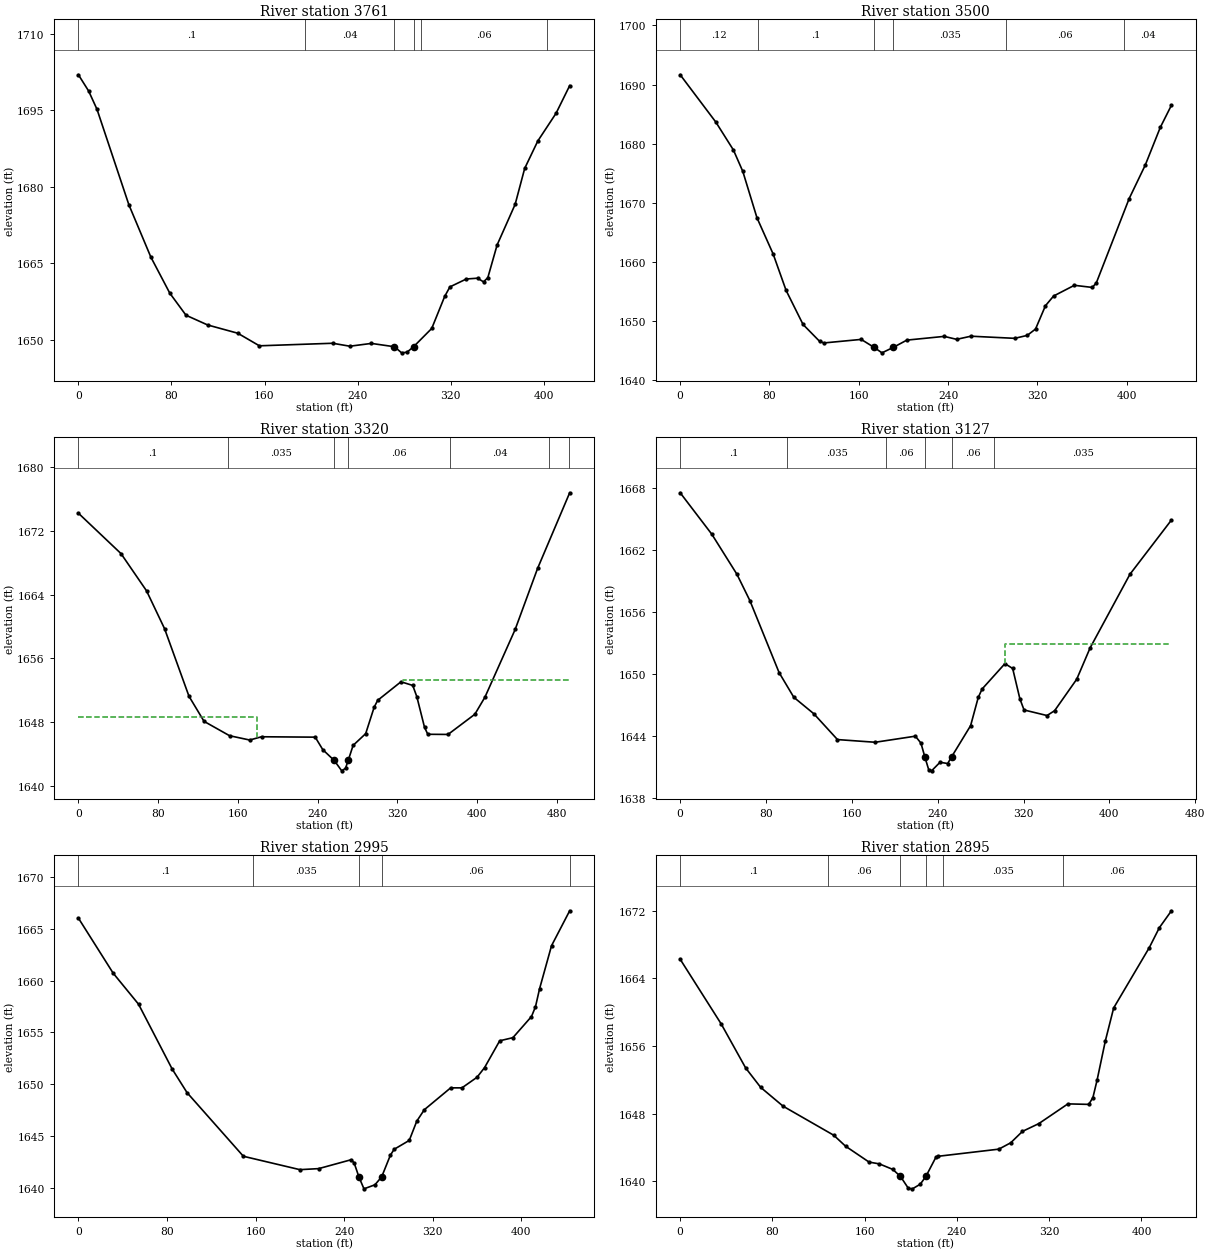
Type RM Length L Ch R = 1 ,3761    ,258.9,260.8,259.3
XS GIS Cut Line= 4
2026857.70814287202668.8575128912026810.84590985 202750.86642069
2026690.76143771202979.3198066992026652.68587338203037.897597983
#Sta/Elev= 30
       0 1701.99     8.8  1698.8      16  1695.2    43.4 1676.47    62.3  1666.2
    78.6 1659.12    92.5  1654.8   111.1 1652.89     137 1651.27   155.6  1648.8
   218.6  1649.3   233.4 1648.72   251.9 1649.27  271.751648.615   277.9 1647.42
   282.5 1647.54  288.151648.615   303.8 1652.21   314.9 1658.48   319.4 1660.36
   333.5 1661.91   343.2 1662.07   348.3 1661.35     352 1662.16     360 1668.59
   375.5 1676.56   383.7 1683.61     395    1689   410.7 1694.44   422.4 1699.86
#Mann= 6 ,-1 , 0
       0      .1       0  194.45     .04       0  271.75    .045       0
  288.15     .04       0  294.45     .06       0  402.55      .1       0
Bank Sta=271.75,288.15
XS Rating Curve= 0 ,0
Exp/Cntr(USF)=0,0
Exp/Cntr=0.3,0.1

Type RM Length L Ch R = 1 ,3500    ,181.4,180,180.7
XS GIS Cut Line= 4
2026714.19255423202580.9908259652026649.75698382202660.070844199
2026538.45918038202868.0220032582026497.45472648202961.746469313
#Sta/Elev= 30
       0 1691.65      32 1683.64    47.7 1678.94    56.1 1675.33    68.8 1667.49
    83.3 1661.37    94.9 1655.22   110.1 1649.46   124.9 1646.62   128.7 1646.34
   162.2 1646.94  173.661645.604   180.8 1644.67  191.081645.603   203.1 1646.82
   236.6 1647.45   247.7 1646.95   260.5 1647.48   299.8 1647.12     311 1647.62
   318.4 1648.69   327.3 1652.63   334.6 1654.27   353.2 1656.08   369.3 1655.72
   372.9  1656.5   402.3 1670.73   416.7 1676.38   430.2 1682.76   440.2 1686.51
#Mann= 6 ,-1 , 0
       0     .12       0      70      .1       0  173.66    .045       0
  191.08    .035       0  292.01     .06       0  397.87     .04       0
Bank Sta=173.66,191.08
XS Rating Curve= 0 ,0
Exp/Cntr(USF)=0,0
Exp/Cntr=0.3,0.1

Type RM Length L Ch R = 1 ,3320    ,184.8,193.1,203
XS GIS Cut Line= 4
2026588.25030297202519.4841451162026488.66805778202639.568617249
2026409.58803955202774.2975372032026368.58358565202950.030911056
#Sta/Elev= 30
       0 1674.19    42.7 1669.13    68.3 1664.47    86.4 1659.72   110.9 1651.25
     126 1648.11   151.6 1646.31   171.8 1645.77  183.67 1646.18   237.5 1646.13
   245.1 1644.56  256.531643.213   264.1 1641.91   267.9 1642.24  270.561643.211
   275.5  1645.1   288.1 1646.57   296.6 1649.88   300.1 1650.74   323.5 1653.07
   335.3 1652.61   339.4  1651.2   347.1 1647.37   350.4 1646.49   370.7 1646.47
   397.6    1649   407.7 1651.14     438 1659.62   460.5 1667.27   492.7 1676.75
#Mann= 7 ,-1 , 0
       0      .1       0     150    .035       0  256.53    .045       0
  270.56     .06       0  372.23     .04       0  472.23    .035       0
  492.23      .1       0
#XS Ineff= 2 , 0
          179.24  1648.7  325.21         1653.25
Permanent Ineff=
       F       F
Bank Sta=256.53,270.56
XS Rating Curve= 0 ,0
Exp/Cntr(USF)=0,0
Exp/Cntr=0.3,0.1

Type RM Length L Ch R = 1 ,3127    ,129.8,131.7,131.8
XS GIS Cut Line= 4
2026535.53029081202484.3374703462026444.73471432202531.199703373
2026236.78355526  202619.06639032026116.69908313202668.857512891
#Sta/Elev= 30
       0 1667.56    29.5 1663.54    52.9 1659.66      65  1657.1    92.2 1650.13
   105.9 1647.74   124.6 1646.14   146.6 1643.64   181.8 1643.38   219.2 1643.97
   224.4  1643.3  228.011641.969   231.7  1640.7   234.3 1640.61   242.2 1641.44
   249.3 1641.32  252.981641.968   270.7 1644.99   277.8 1647.72   281.4 1648.54
   302.7    1651   309.9 1650.53   316.6  1647.6   320.5 1646.51   341.9 1645.97
     349 1646.44   369.6 1649.49   382.1 1652.53   419.2 1659.66   457.9 1664.92
#Mann= 6 ,-1 , 0
       0      .1       0     100    .035       0  192.18     .06       0
  228.01    .045       0  252.98     .06       0  292.18    .035       0
#XS Ineff= 2 , 0
                          303.02         1652.94
Permanent Ineff=
       F       F
Bank Sta=228.01,252.98
XS Rating Curve= 0 ,0
Exp/Cntr(USF)=0,0
Exp/Cntr=0.3,0.1

Type RM Length L Ch R = 1 ,2995    ,99.2,99.9,98.3
XS GIS Cut Line= 4
2026523.90802363202412.5641275092026427.16137693202428.688568626
 2026151.8457579202504.8396972952026097.56953584202530.245588474
#Sta/Elev= 30
       0 1666.03    31.4 1660.72    54.3 1657.73    84.6 1651.49    98.1  1649.2
     149 1643.06     200 1641.77     217 1641.87   246.4 1642.73   249.1  1642.4
   253.4 1641.05   257.9 1639.92   267.8 1640.31   273.91641.077   281.7 1643.15
   285.1 1643.73   298.8 1644.59   305.6 1646.45   312.4 1647.55   336.2 1649.66
   346.4 1649.66     360 1650.68   366.8 1651.61   380.5  1654.2   392.4  1654.5
   409.2 1656.54   412.8 1657.48   416.5 1659.22   427.3 1663.37   443.7 1666.74
#Mann= 5 ,-1 , 0
       0      .1       0  158.08    .035       0   253.4    .045       0
   273.9     .06       0  443.66    .035       0
Bank Sta=253.4,273.9
XS Rating Curve= 0 ,0
Exp/Cntr(USF)=0,0
Exp/Cntr=0.3,0.1

Type RM Length L Ch R = 1 ,2895    ,45.3,44.4,44.4
XS GIS Cut Line= 4
2026491.72025114202333.8618983312026376.31723133202358.311690663
2026199.70519061202408.3957022112026086.43986364202459.971877884
#Sta/Elev= 30
       0 1666.25    35.6  1658.6    56.8  1653.4    69.8 1651.11    89.2 1648.89
   133.2 1645.45   143.4 1644.16   163.8 1642.28   172.7 1642.07   184.3 1641.42
     191 1640.59   197.9 1639.17   201.4 1639.12   208.2 1639.67   213.11640.595
   221.8 1642.87   223.2 1642.96   276.3 1643.81   286.6 1644.56   296.8 1645.91
     311 1646.83   336.2 1649.16   354.3  1649.1   357.9 1649.91   361.5 1651.96
   368.7 1656.62   375.9  1660.5   406.8 1667.63   415.5 1669.98     426 1671.98
#Mann= 6 ,-1 , 0
       0      .1       0  127.96     .06       0     191    .045       0
   213.1     .06       0  227.96    .035       0  331.54     .06       0
#XS Ineff= 2 ,-1
  155.17  186.66 1640.93  218.14  253.37 1641.06
Permanent Ineff=
       F       F
Bank Sta=191,213.1
XS Rating Curve= 0 ,0
Exp/Cntr(USF)=0,0
Exp/Cntr=0.3,0.1