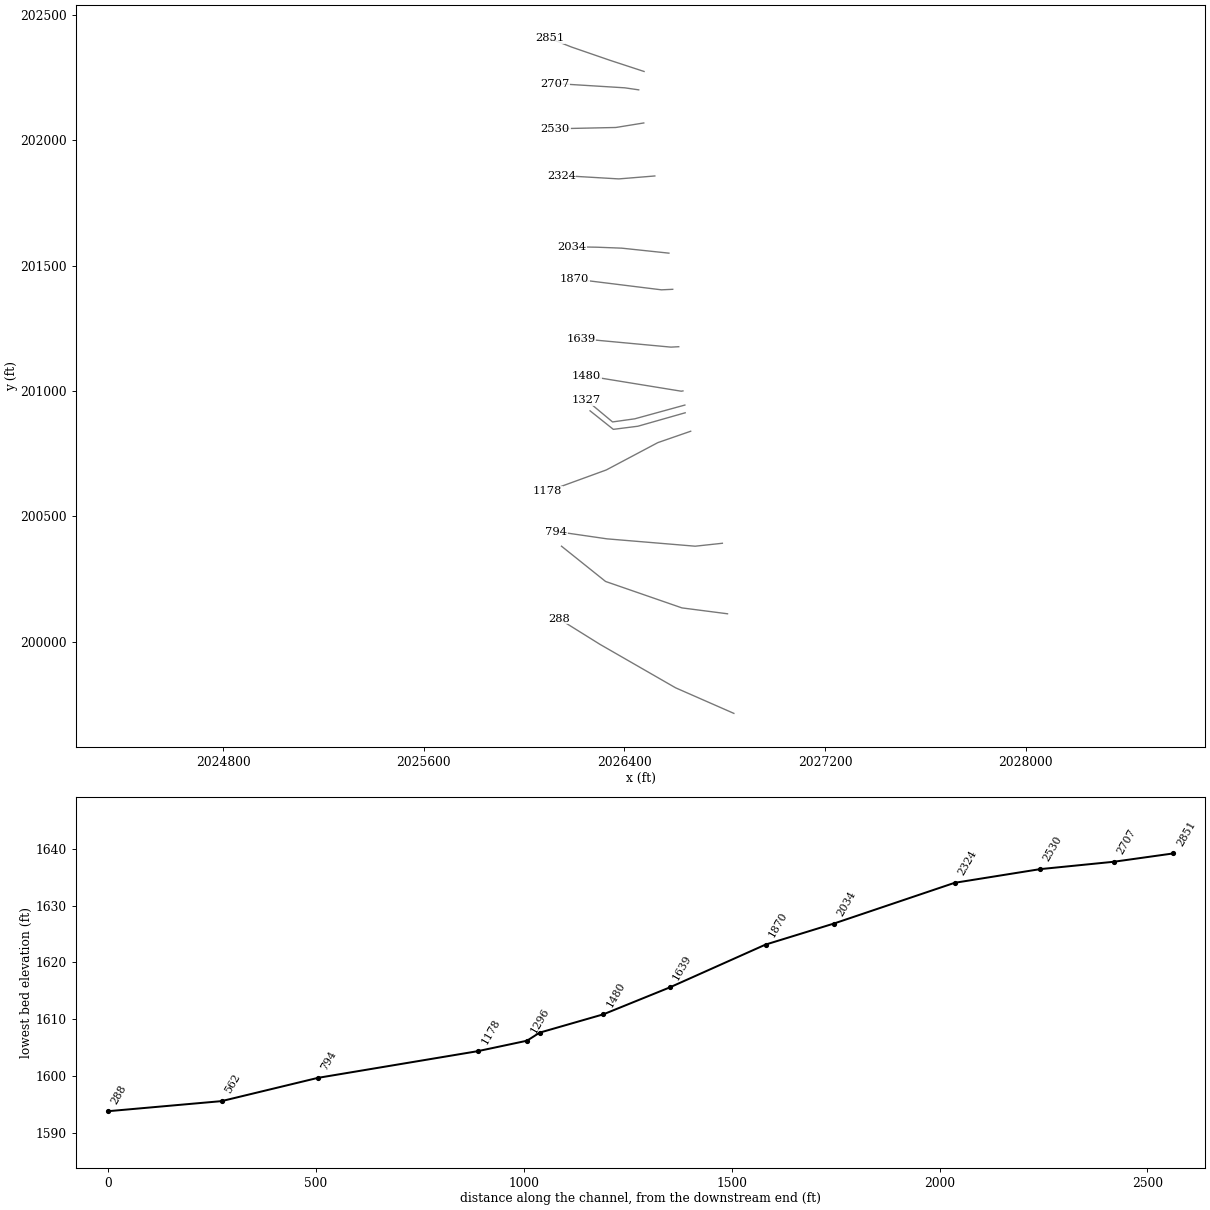
HEC-RAS study BRDSHWCK2_A.prj: BRDSHWCK2_A

--- BRDSHWCK2_A.g01 (geometry) --- (continued)

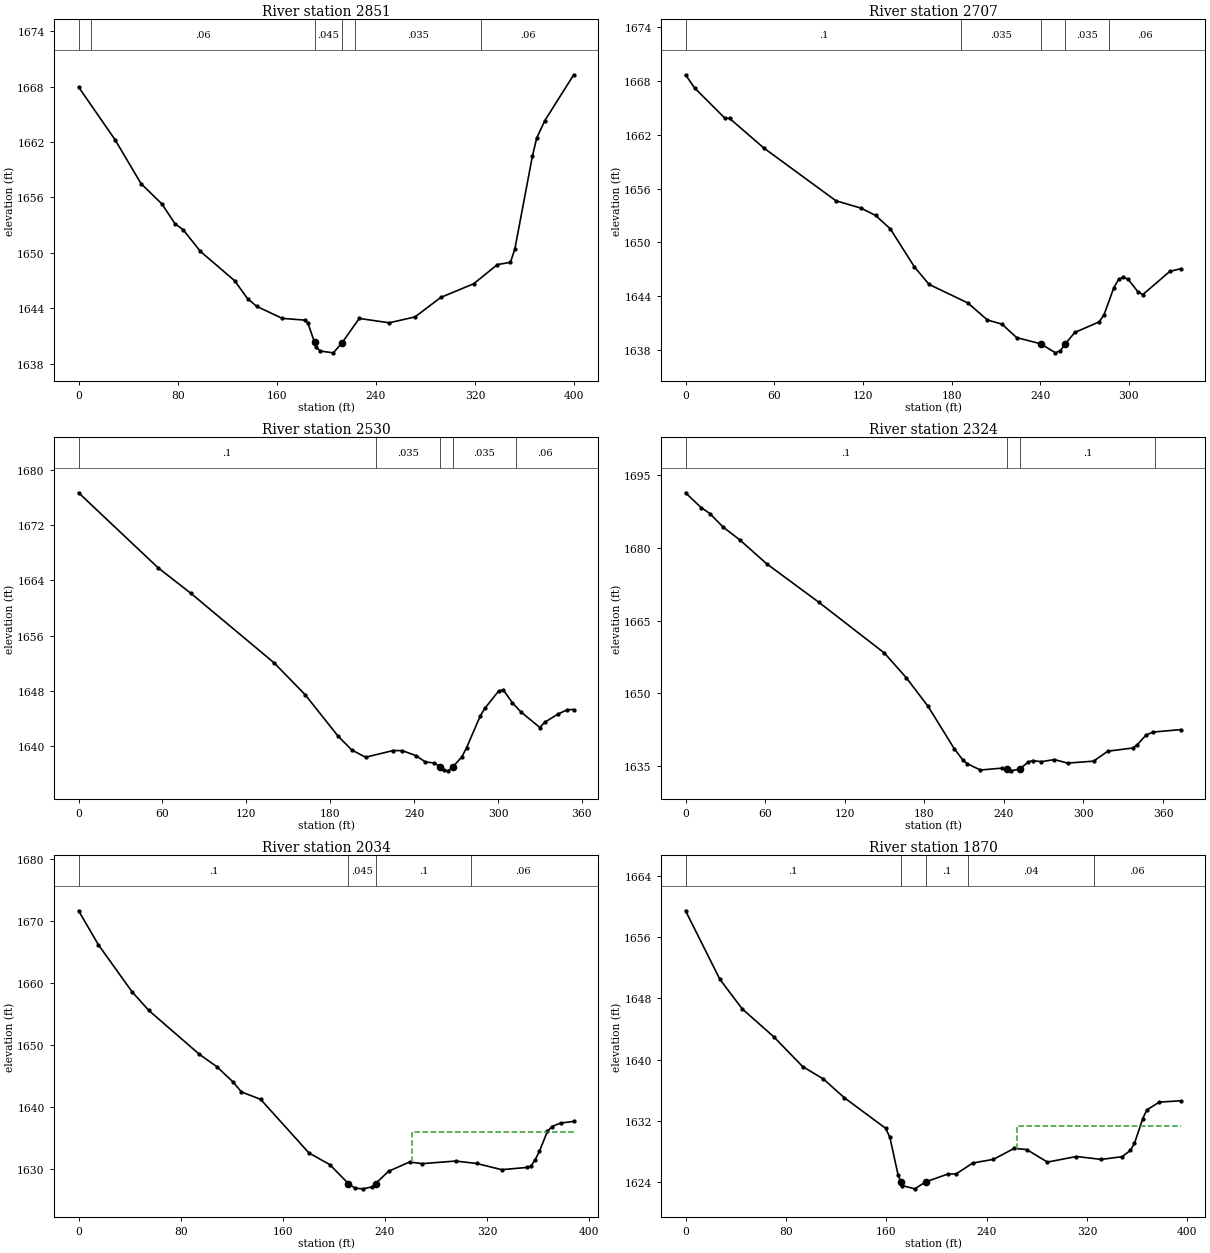
Type RM Length L Ch R = 1 ,2851    ,132.8,143.4,145
XS GIS Cut Line= 4
2026478.17635455202274.1585881542026342.04922343202318.771681546
2026189.16118818202371.4916937022026100.92314994202406.301195025
#Sta/Elev= 30
       0 1667.94    29.4 1662.25    50.4  1657.5    67.3 1655.29    77.7 1653.18
    84.6 1652.48    98.4 1650.16     126 1646.99   136.4 1645.06   143.8 1644.22
   164.4 1642.92   182.5 1642.73   185.1 1642.42   190.5 1640.34   191.9 1639.78
   195.3 1639.38   205.7 1639.19   212.81640.287   226.6 1642.91   250.9 1642.44
   271.7 1643.08   292.5 1645.19     319 1646.66   338.2 1648.74   348.7 1648.98
   352.3 1650.45   366.4 1660.44   369.9 1662.42   376.5 1664.32   399.8 1669.27
#Mann= 6 ,-1 , 0
       0      .1       0      10     .06       0   190.5    .045       0
   212.8     .06       0  223.25    .035       0  324.97     .06       0
#XS Ineff= 2 ,-1
  156.52  185.31  1640.7  218.29  224.29 1640.76
Permanent Ineff=
       F       F
Bank Sta=190.5,212.8
XS Rating Curve= 0 ,0
Exp/Cntr(USF)=0,0
Exp/Cntr=0.3,0.1

Type RM Length L Ch R = 1 ,2707    ,174.4,177.2,177.3
XS GIS Cut Line= 3
2026456.81238024202200.8912209152026400.80137086202209.021851309
2026122.90162729202226.211526169
#Sta/Elev= 30
       0 1668.65     6.1 1667.19    26.5 1663.84    29.8  1663.8      53  1660.5
   101.7 1654.64   118.8 1653.81   128.6    1653   138.5 1651.52   154.9 1647.27
   164.8 1645.33   191.1 1643.26   204.2 1641.38   214.1 1640.91     224 1639.42
   240.4 1638.72   250.3 1637.72   253.6 1637.97   256.8  1638.7   263.4 1639.99
   279.8 1641.16   283.1 1641.93   289.7 1644.93     293  1645.9   296.3 1646.14
   299.6 1645.88   306.1  1644.5   309.4  1644.2   327.6 1646.77     335 1647.08
#Mann= 5 ,-1 , 0
       0      .1       0   186.6    .035       0   240.4    .045       0
   256.8    .035       0   286.6     .06       0
Bank Sta=240.4,256.8
XS Rating Curve= 0 ,0
Exp/Cntr(USF)=0,0
Exp/Cntr=0.3,0.1

Type RM Length L Ch R = 1 ,2530    ,211.3,205.6,204.3
XS GIS Cut Line= 3
2026476.95417586202068.9103791282026365.65469609202050.861814841
2026124.29447301 202045.67127241
#Sta/Elev= 30
       0 1676.69    56.9 1665.82    80.2 1662.15   139.8 1652.07   162.1 1647.44
   185.6 1641.45   195.5 1639.43   205.3 1638.39     225 1639.36   231.6 1639.34
   241.4 1638.62     248 1637.71   254.5 1637.56   258.5 1637.03   261.1 1636.49
   264.4 1636.42   267.7 1636.98   274.2 1638.45   277.5 1639.75   287.3 1644.34
   290.6 1645.47   300.5 1647.98   303.8 1648.15   310.3 1646.28   316.3 1644.98
     330 1642.69   333.3 1643.43   343.1 1644.66   349.7 1645.27   354.2  1645.3
#Mann= 5 ,-1 , 0
       0      .1       0  212.75    .035       0   258.5    .045       0
   267.7    .035       0  312.75     .06       0
Bank Sta=258.5,267.7
XS Rating Curve= 0 ,0
Exp/Cntr(USF)=0,0
Exp/Cntr=0.3,0.1

Type RM Length L Ch R = 1 ,2324    ,287.3,290.5,291.6
XS GIS Cut Line= 3
2026521.02195743 201857.532125832026377.37025434201845.839545346
2026148.56253503201859.298822952
#Sta/Elev= 30
       0 1691.43    11.7 1688.38    18.3 1687.15    28.2 1684.38    41.3 1681.61
    61.1 1676.78   100.6  1668.8     150 1658.32   166.4 1653.25   182.8 1647.35
   202.5 1638.62   209.1 1636.23   212.4 1635.48   222.3 1634.18   238.7 1634.57
     242 1634.34   245.3 1634.01   251.8 1634.37   258.4 1635.82   261.7 1636.13
   268.3  1635.9   278.1 1636.34     288 1635.61   307.7 1636.01   318.3 1638.06
   337.3 1638.73   340.6 1639.41   347.2 1641.39   352.4 1642.02   373.3 1642.52
#Mann= 4 ,-1 , 0
       0      .1       0     242    .045       0   251.8      .1       0
  354.13     .06       0
Bank Sta=242,251.8
XS Rating Curve= 0 ,0
Exp/Cntr(USF)=0,0
Exp/Cntr=0.3,0.1

Type RM Length L Ch R = 1 ,2034    ,162.6,164.1,161.3
XS GIS Cut Line= 4
2026577.20409498201549.8097434882026388.93680085201569.722630367
2026290.59510915201573.5050031252026190.46743562201575.274043293
#Sta/Elev= 30
       0 1671.66    15.5 1666.18    41.8 1658.62      55 1655.59    94.6 1648.52
   108.2 1646.54     121 1644.06   127.6 1642.45   142.6 1641.26   180.4 1632.63
   196.9 1630.72   211.3 1627.69   216.6 1626.93   222.8 1626.83   229.6 1627.13
   232.71627.687   242.8 1629.66   259.3 1631.16   269.1 1630.89   295.4 1631.31
   311.8 1630.92   331.5 1629.92   351.2 1630.28   354.5 1630.54   357.7 1631.53
     361 1632.87   367.3 1636.09   370.8 1636.88   377.8 1637.44   387.9  1637.7
#Mann= 4 ,-1 , 0
       0      .1       0   211.3    .045       0   232.7      .1       0
  307.73     .06       0
#XS Ineff= 2 , 0
                          260.87         1636.07
Permanent Ineff=
       F       F
Bank Sta=211.3,232.7
XS Rating Curve= 0 ,0
Exp/Cntr(USF)=0,0
Exp/Cntr=0.3,0.1

Type RM Length L Ch R = 1 ,1870    ,229.9,230.6,230.8
XS GIS Cut Line= 3
2026592.41263773201405.6618421642026547.24584907201403.577221149
2026200.52990915201446.580748581
#Sta/Elev= 30
       0 1659.42    27.3 1650.49    45.2 1646.61    70.2 1642.99    93.3 1639.09
   109.9 1637.46   126.4 1635.04   159.4 1631.04   162.8 1629.89   169.4 1624.93
   171.51624.049   172.7 1623.56   182.6 1623.13   191.61624.045     209 1625.06
   215.6 1625.07   228.9  1626.5   245.4 1626.98   261.9 1628.41   271.9 1628.26
   288.4 1626.62   311.5 1627.35   331.4 1626.97   347.9 1627.33   354.5 1628.14
   357.8 1629.07   364.4 1632.31   367.7 1633.44   377.6 1634.45   394.6 1634.62
#Mann= 5 ,-1 , 0
       0      .1       0   171.5    .045       0   191.6      .1       0
  225.21     .04       0  325.21     .06       0
#XS Ineff= 2 , 0
                          264.42          1631.3
Permanent Ineff=
       F       F
Bank Sta=171.5,191.6
XS Rating Curve= 0 ,0
Exp/Cntr(USF)=0,0
Exp/Cntr=0.3,0.1

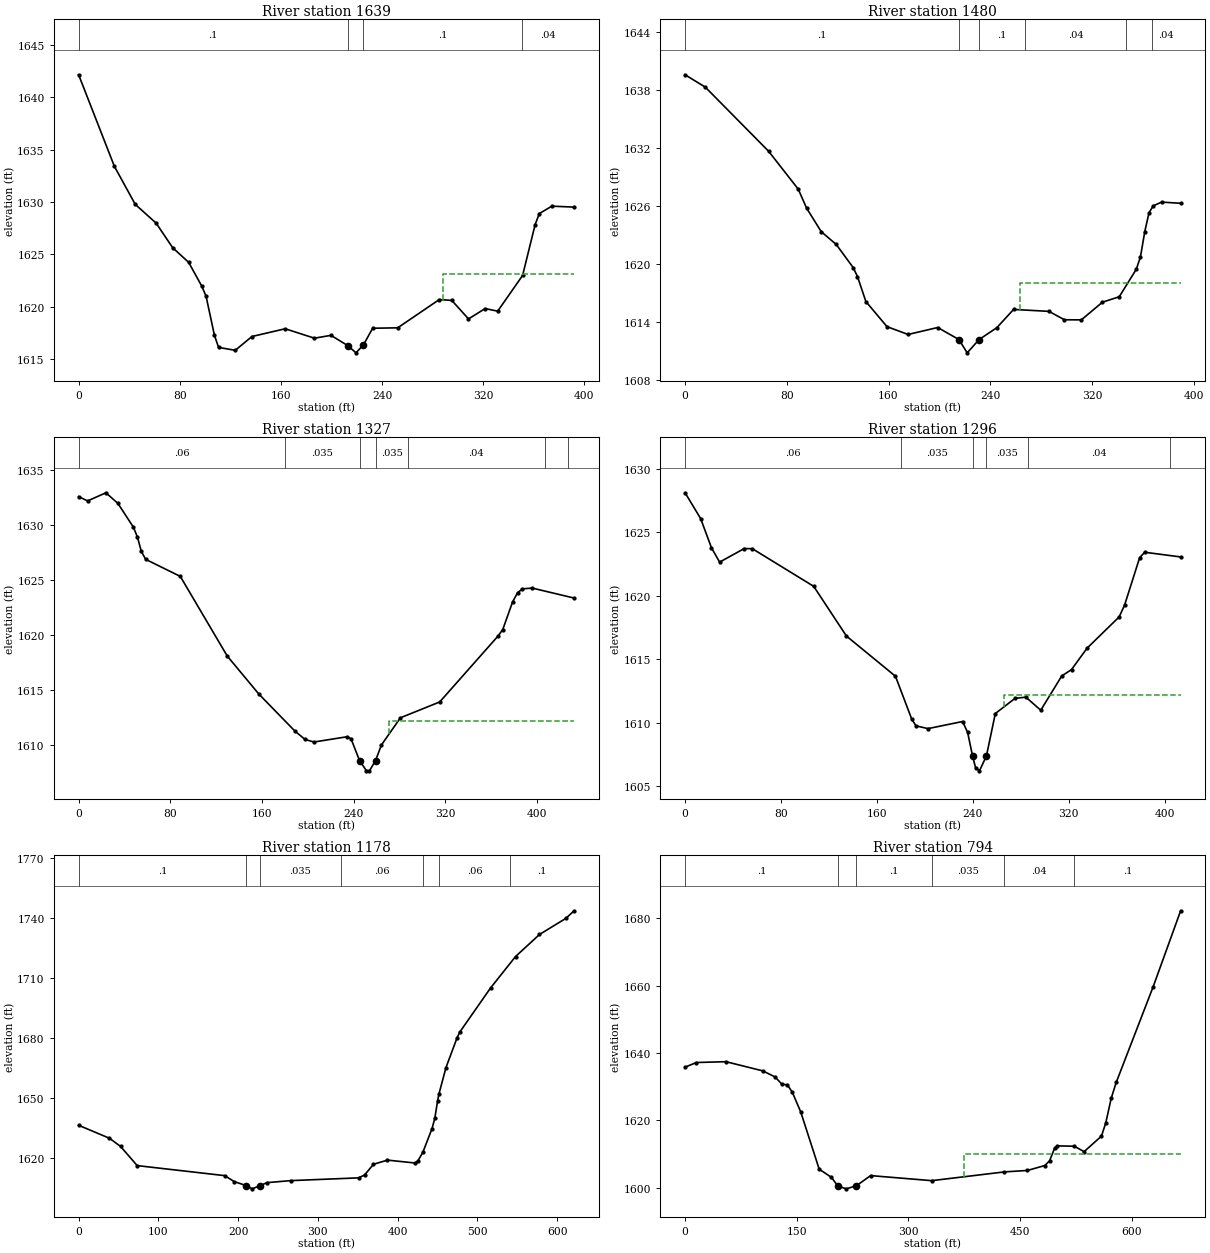
Type RM Length L Ch R = 1 ,1639    ,160.4,159.3,158
XS GIS Cut Line= 3
2026616.36677566201176.786979547 2026585.3214134 201175.12383514
2026225.99449949201208.549594574
#Sta/Elev= 30
       0 1642.14    28.3 1633.39    44.8 1629.76    61.3 1627.97    74.4 1625.62
      87 1624.23    97.5 1621.93   100.8 1620.99   107.4 1617.27   110.7  1616.1
   123.9 1615.82   137.1 1617.14   163.4 1617.88   186.5 1616.98   199.6 1617.25
   212.8 1616.28   219.4 1615.58   225.31616.342   232.6 1617.93   252.4 1617.97
   285.3 1620.67   295.2 1620.59   308.4 1618.82   321.6 1619.81   331.5 1619.56
   351.2 1622.97   361.1 1627.82   364.4 1628.88   374.3 1629.59     392  1629.5
#Mann= 4 ,-1 , 0
       0      .1       0   212.8    .045       0   225.3      .1       0
  351.09     .04       0
#XS Ineff= 2 , 0
                          287.84         1623.09
Permanent Ineff=
       F       F
Bank Sta=212.8,225.3
XS Rating Curve= 0 ,0
Exp/Cntr(USF)=0,0
Exp/Cntr=0.3,0.1

Type RM Length L Ch R = 1 ,1480    ,149.3,153.3,156.6
XS GIS Cut Line= 3
2026633.24200874201000.593268494 2026626.3258673200999.390461287
2026248.49911352201060.897142136
#Sta/Elev= 30
       0 1639.61    15.9 1638.33    65.7  1631.7      89 1627.78    95.6 1625.81
   107.1 1623.38   118.9 1622.06   132.2 1619.67   135.6 1618.74   142.2 1616.16
   158.8 1613.56   175.4 1612.75   198.7 1613.47   215.41612.225   221.9 1610.85
   231.21612.218   245.2 1613.45   258.4 1615.34   286.2 1615.14   298.4 1614.27
   311.7 1614.26   328.3 1616.09   341.5 1616.65   354.9 1619.49   358.2 1620.78
   361.6  1623.4   364.9 1625.33   368.2 1626.05   374.8 1626.44   389.8 1626.32
#Mann= 6 ,-1 , 0
       0      .1       0   215.4    .045       0   231.2      .1       0
  267.02     .04       0  347.02      .1       0  367.02     .04       0
#XS Ineff= 2 , 0
                          263.35         1618.04
Permanent Ineff=
       F       F
Bank Sta=215.4,231.2
XS Rating Curve= 0 ,0
Exp/Cntr(USF)=0,0
Exp/Cntr=0.3,0.1

Type RM Length L Ch R = 1 ,1327    ,30.7,30.4,30.7
XS GIS Cut Line= 4
2026640.84230523200944.1645924892026441.16336739 200889.31715892
2026352.44104346200876.8649029292026248.28374707200963.728157651
#Sta/Elev= 30
       0 1632.54     7.8 1632.15    23.8 1632.89    34.3 1631.92    47.8 1629.76
    51.3 1628.86    54.7 1627.56    58.5 1626.84    88.7 1625.29   129.6 1618.06
   157.2  1614.6   188.8 1611.22   197.6 1610.47   205.3 1610.24   234.3 1610.72
   237.6 1610.54   245.11608.549   250.9 1607.65   253.7 1607.62     2591608.546
   264.1 1609.96   280.7 1612.44     315 1613.88   365.8 1619.86     370 1620.46
   378.6 1622.98   382.9  1623.8   387.2 1624.16   395.7 1624.23   432.3 1623.32
#Mann= 7 ,-1 , 0
       0     .06       0     180    .035       0   245.1    .045       0
     259    .035       0  287.07     .04       0  406.67      .1       0
  426.67     .04       0
#XS Ineff= 2 , 0
          238.02 1610.14  270.82         1612.17
Permanent Ineff=
       F       F
Bank Sta=245.1,259
XS Rating Curve= 0 ,0
Exp/Cntr(USF)=0,0
Exp/Cntr=0.3,0.1

Type RM Length L Ch R = 1 ,1296    ,112.4,118.3,120.1
XS GIS Cut Line= 4
2026642.05553394200913.3437366082026453.61562339200859.743050941
2026355.55410746 200847.290794952026262.78949448200921.165159468
#Sta/Elev= 30
       0 1628.13      13 1626.09      22 1623.79    28.8 1622.66    49.3 1623.73
    56.1 1623.72   107.3 1620.75   134.6 1616.83   175.5 1613.66   189.1 1610.27
   192.6 1609.75   202.6 1609.53   231.5 1610.09   235.7 1609.23   239.8 1607.38
   242.3 1606.45   245.6  1606.2   251.41607.382   258.8 1610.72   275.3 1611.92
   284.3 1612.01   296.7 1610.98   314.2 1613.68   322.4 1614.19   335.3 1615.87
   362.1 1618.34   366.6 1619.26   379.2 1623.01   383.4 1623.44   413.4 1623.07
#Mann= 6 ,-1 , 0
       0     .06       0     180    .035       0   239.8    .045       0
   251.4    .035       0  285.91     .04       0  404.76      .1       0
#XS Ineff= 2 , 0
          230.13 1609.72  266.12         1612.21
Permanent Ineff=
       F       F
Bank Sta=239.8,251.4
XS Rating Curve= 0 ,0
Exp/Cntr(USF)=0,0
Exp/Cntr=0.3,0.1

Type RM Length L Ch R = 1 ,1178    ,394.6,384.3,376.6
XS GIS Cut Line= 4
 2026664.0006999200839.7436822032026532.99875533200794.368706987
2026327.53653148200685.4114670642026092.50019964200599.802207125
#Sta/Elev= 30
       0  1636.2    38.7 1629.69    52.6 1625.59    73.4    1616   183.2 1610.97
   195.1 1607.98   210.41605.949   217.4 1604.36   227.41605.926     236 1607.46
   265.7 1608.47   351.1 1609.86   358.5  1611.3   369.7 1616.66   387.2 1618.75
   422.1 1617.29   425.6 1618.52   431.5  1622.6   443.1 1634.54   446.6 1639.73
   450.1 1648.51   451.9 1652.07   460.5 1665.02   474.5 1680.05     478 1682.95
   516.4 1704.95   547.8 1720.73   577.8 1731.76   610.7 1739.79   621.3 1743.64
#Mann= 7 ,-1 , 0
       0      .1       0   210.4    .045       0   227.4    .035       0
  328.64     .06       0   431.2      .1       0   451.2     .06       0
   541.2      .1       0
Bank Sta=210.4,227.4
XS Rating Curve= 0 ,0
Exp/Cntr(USF)=0,0
Exp/Cntr=0.3,0.1

Type RM Length L Ch R = 1 ,794     ,236.1,231.8,228.8
XS GIS Cut Line= 4
 2026790.3436829200393.1103214942026681.97476902200381.394763237
2026330.50802132 200410.683658882026128.41464138200439.972554522
#Sta/Elev= 30
       0 1635.81    15.3 1637.18    54.9 1637.42   104.4 1634.69   120.9 1632.89
   130.2 1630.71   137.4 1630.56     144 1628.39   155.4 1622.49   180.2  1605.5
   196.6 1603.08  205.13 1600.54   216.3 1599.66  229.981600.541   249.3 1603.59
   331.4 1602.09   429.1 1604.69     460 1605.12   483.2 1606.57   489.8 1607.97
   496.5 1611.73   499.8 1612.43     523 1612.31   536.2 1610.71   559.5 1615.31
   565.3 1619.25   572.7 1626.63   579.3 1631.25   629.1 1659.75   665.9 1682.24
#Mann= 6 ,-1 , 0
       0      .1       0  205.13    .045       0  229.98      .1       0
   331.4    .035       0   429.1     .04       0     523      .1       0
#XS Ineff= 2 , 0
                             375            1610
Permanent Ineff=
       F       F
Bank Sta=205.13,229.98
XS Rating Curve= 0 ,0
Exp/Cntr(USF)=0,0
Exp/Cntr=0.3,0.1

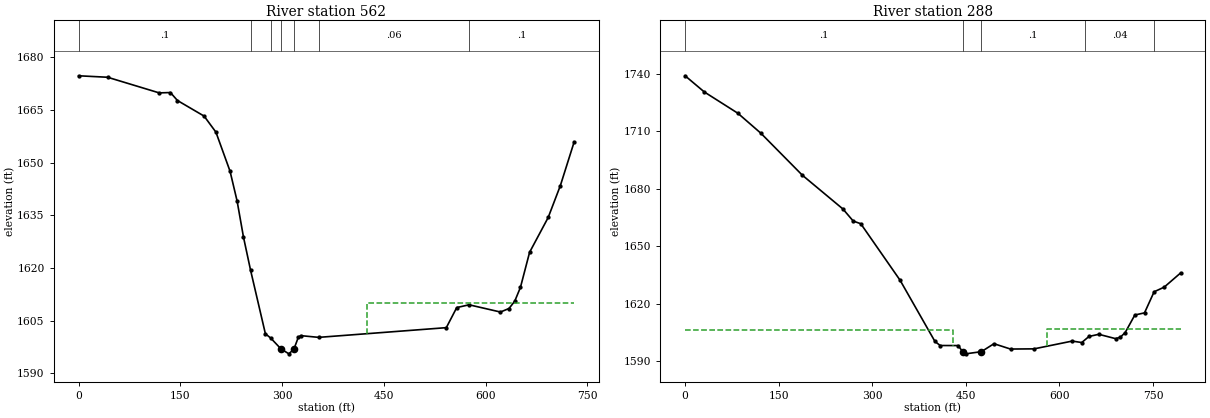
Type RM Length L Ch R = 1 ,562     ,277.2,273.6,269.1
XS GIS Cut Line= 4
2026810.84590985200111.9369233292026629.25475687200135.368039843
2026324.65024219200240.8080641552026148.91686833200381.394763237
#Sta/Elev= 30
       0  1674.7    42.7 1674.28   118.8 1669.83   135.3 1669.93   145.7 1667.66
     185 1663.22   202.4 1658.65   223.2 1647.54   233.6 1639.07     243  1628.8
   253.4 1619.42   275.3 1601.28   283.2 1600.04  298.361596.948     310 1595.56
  317.44 1596.95   323.9 1600.29   327.4 1600.74   353.9 1600.25     542 1603.01
   557.4 1608.73   575.6 1609.52   621.8 1607.46   634.4 1608.46   642.9 1610.55
   651.3 1614.48   664.8 1624.47   692.2 1634.37   710.1 1643.42   730.5 1655.89
#Mann= 7 ,-1 , 0
       0      .1       0   253.4     .06       0   283.2      .1       0
  298.36    .045       0  317.44      .1       0   353.9     .06       0
   575.6      .1       0
#XS Ineff= 2 , 0
                             425            1610
Permanent Ineff=
       F       F
Bank Sta=298.36,317.44
XS Rating Curve= 0 ,0
Exp/Cntr(USF)=0,0
Exp/Cntr=0.3,0.1

Type RM Length L Ch R = 1 ,288     ,293,287.7,274.5
XS GIS Cut Line= 4
2026836.13195051199714.857231987 2026603.6366969199816.870455509
2026302.34182743199990.0556954412026138.64618969200092.068918963
#Sta/Elev= 30
       0 1738.82    30.8 1730.38    84.6 1719.27   121.4 1708.87   187.9 1686.97
     253 1669.33   269.5 1663.04   281.6 1661.64   344.6 1632.17   400.5 1600.23
   408.9 1598.12   437.8  1598.1  444.781594.905   449.7 1593.78  474.821594.906
   495.1 1599.06   521.6 1596.28   559.4 1596.38   620.4 1600.43   635.8 1599.68
   647.4 1602.85   663.1 1603.97     690 1601.71   697.7 1602.45   705.4 1604.89
   720.9 1614.04   736.4 1615.15   751.8 1626.16   767.9 1628.56   794.3 1635.98
#Mann= 5 ,-1 , 0
       0      .1       0  444.78    .045       0  474.82      .1       0
  641.41     .04       0  751.41      .1       0
#XS Ineff= 2 ,-1
       0  428.65 1606.04  579.94794.2941 1606.67
Permanent Ineff=
       F       F
Bank Sta=444.78,474.82
XS Rating Curve= 0 ,0
Exp/Cntr(USF)=0,0
Exp/Cntr=0.3,0.1