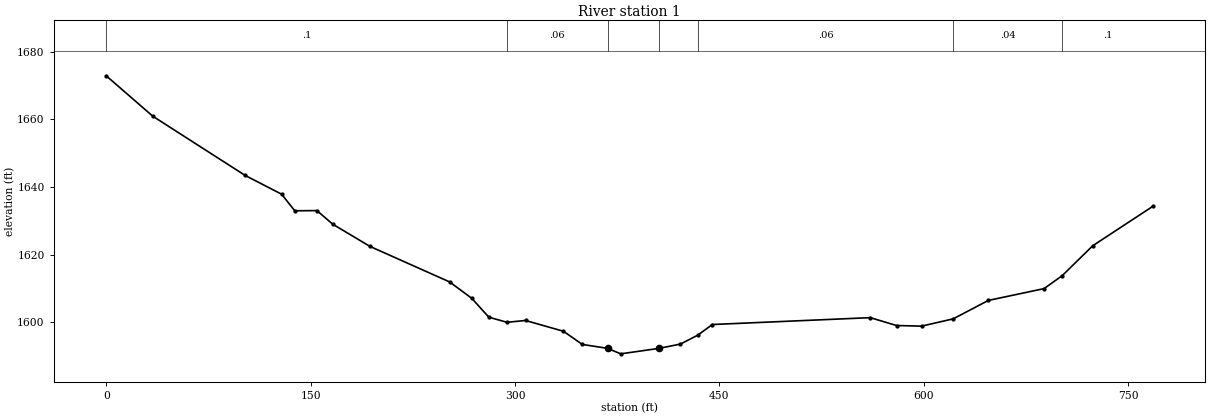
HEC-RAS study BRDSHWCK2_A.prj: BRDSHWCK2_A

--- BRDSHWCK2_A.g01 (geometry) --- (continued)

Type RM Length L Ch R = 1 ,1       ,122.1,83.5,53.2
XS GIS Cut Line= 4
2026578.59061978199403.397455617     2026545.913      199413.274
     2026261.198      199704.795     2026149.964      200011.964
#Sta/Elev= 30
       0  1672.9   34.14 1660.95  101.96 1643.41  128.74 1637.85  138.39 1632.94
  154.63    1633  166.31 1628.96  193.67 1622.38  252.07 1611.88  268.31 1607.03
  280.81 1601.45  294.141599.938  307.76 1600.47   335.6 1597.28  349.43 1593.38
  367.94 1592.23  377.61  1590.6  405.78 1592.22  421.44 1593.49  434.141596.123
  444.88 1599.28  560.78 1601.31  580.05 1598.98  598.41  1598.8  621.631600.953
   647.5 1606.42  688.31  1609.9  701.631613.739  724.03 1622.59  768.32 1634.31
#Mann= 7 ,-1 , 0
       0      .1       0  294.14     .06       0  367.94    .045       0
  405.78    .035       0  434.14     .06       0  621.63     .04       0
  701.63      .1       0
Bank Sta=367.94,405.78
XS Rating Curve= 0 ,0
Exp/Cntr=0.5,0.3
LCMann Table=0

Chan Stop Cuts=-1
Use User Specified Reach Order=0
Composite Channel Slope=5